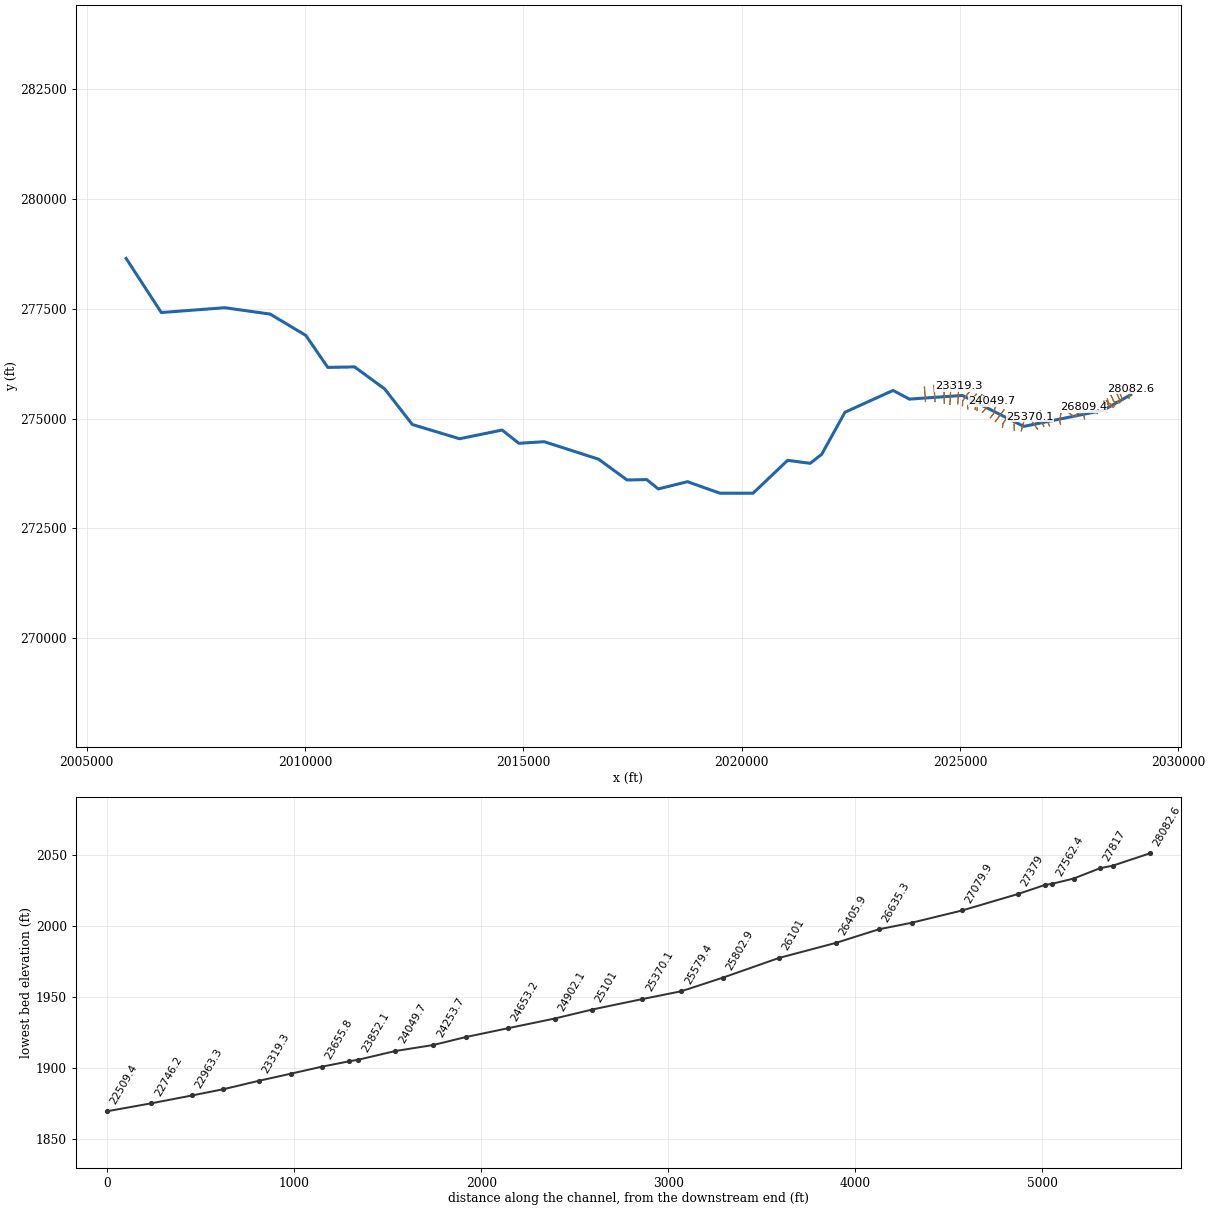
--- LAURELCK.prj (project) ---

Proj Title=LAURELCK
Current Plan=p01
Default Exp/Contr=0,0
English Units
Geom File=g01
Flow File=f01
Plan File=p01
BEGIN DESCRIPTION:
END DESCRIPTION:
DSS Export Rating Curves= 0
DSS Export Rating Curve Sorted= 0
DSS Export Volume Flow Curves= 0
DXF OffsetX= 0
DXF OffsetY= 0
DXF ScaleX= 0
DXF ScaleY= 0

--- LAURELCK.p01 (plan) ---

Plan Title=Floodplain
Program Version=4.10
Geom File=g01
Flow File=f01
Subcritical Flow
K Sum by GR= 0
Std Step Tol= 0.01
Critical Tol= 0.01
Num of Std Step Trials= 20
Max Error Tol= 0.3
Flow Tol Ratio= 0.001
Split Flow NTrial= 30
Split Flow Tol= 0.02
Split Flow Ratio= 0.02
Log Output Level= 0
Friction Slope Method= 1
Unsteady Friction Slope Method= 2
Unsteady Bridges Friction Slope Method= 1
Parabolic Critical Depth
Global Vel Dist= 0 , 0 , 0
Global Log Level= 0
CheckData=True
Encroach Param=-1 ,0,0, 0
Run HTab= 0
Run UNet= 0
Run PostProcess= 0
Run WQNet= 0
UNET Theta= 0
UNET Theta Warmup= 0
UNET ZTol= 0
UNET ZSATol= 0
UNET MxIter= 0
UNET MaxInSteps= 0
UNET DtIC= 0
UNET DtMin= 0
UNET MaxCRTS= 0
UNET WFStab= 0
UNET SFStab= 0
UNET WFX= 1
UNET SFX= 1
UNET DSS MLevel= 1
UNET DZMax Abort= 0
UNET Convert EG Bridges= 0
UNET Use Existing IB Tables= 0
UNET Froude Reduction=False
UNET Froude Limit= 0
UNET Froude Power= 0
UNET Time Slicing=0,0, 5
UNET Junction Losses=0
DSS File=dss
Write IC File= 0
Write IC File at Sim End=0
Echo Input=False
Echo Parameters=False
Echo Output=False
Write Detailed= 0
WQ AD Non Conservative
WQ ULTIMATE=-1
WQ Max Comp Step=1HOUR
WQ Output Interval=15MIN
WQ Output Selected Increments= 0
WQ Output face flow=0
WQ Output face velocity=0
WQ Output face area=0
WQ Output face dispersion=0
WQ Output cell volume=0
WQ Output cell surface area=0
WQ Output cell continuity=0
WQ Output cumulative cell continuity=0
WQ Output face conc=0
WQ Output face dconc_dx=0
WQ Output face courant=0
WQ Output face peclet=0
WQ Output face adv mass=0
WQ Output face disp mass=0
WQ Output cell mass=0
WQ Output cell source sink temp=0
WQ Output cell source sink nsm=0
WQ Output MaxMinRange=-1
WQ Daily Max Min Mean=-1
WQ Daily Range=0
WQ Daily Time=0
WQ Create Restart=0
WQ Fixed Restart=0
WQ System Summary=0
WQ Use Fixed Temperature=0
Sorting and Armoring Iterations= 10
XS Update Threshold= 0.02
Hydraulics Update Threshold= 0.02
Energy Slope Method= 1
Volume Change Method= 0
XS Weighting Method= 0
Number of US Weighted Cross Sections= 1
Number of DS Weighted Cross Sections= 1
Upstream XS Weight=0.25
Main XS Weight=0.5
Downstream XS Weight=0.25
Number of DS XS's Weighted with US Boundary= 1
Upstream Boundary Weight= 1
Weight of XSs Associated with US Boundary= 0
Number of US XS's Weighted with DS Boundary= 1
Downstream Boundary Weight= 0.5
Weight of XSs Associated with DS Boundary= 0.5
Sediment Output Level= 4
Mass or Volume Output= 0
Output Increment Type= 1
Profile and TS Output Increment= 10
XS Output Flag= 0
XS Output Increment= 10
Disregard all LS=0
Disregard all Conn=0
Disregard all Breaches=0
Disregard all Pumps=0

--- LAURELCK.f01 (steady flow) ---

Flow Title=NFF Regression Equation
Program Version=4.10
Number of Profiles= 1
Profile Names=P100yr
River Rch & RM=LAURELCK,Main            ,28082.6
587.7827
River Rch & RM=LAURELCK,Main            ,26809.4
630.8679
River Rch & RM=LAURELCK,Main            ,24653.2
692.5392
River Rch & RM=LAURELCK,Main            ,23655.8
 759.949
River Rch & RM=LAURELCK,Main            ,21145
819.5517
River Rch & RM=LAURELCK,Main            ,20848.7
970.4339
River Rch & RM=LAURELCK,Main            ,18519.2
1704.342
River Rch & RM=LAURELCK,Main            ,18519.2
990.0989
River Rch & RM=LAURELCK,Main            ,14662.6
1880.426
River Rch & RM=LAURELCK,Main            ,8801.6
2088.298
River Rch & RM=LAURELCK,Main            ,5906
2316.289
River Rch & RM=LAURELCK,Main            ,3875.2
2492.431
River Rch & RM=LAURELCK,Main            ,155.7
2722.431
Boundary for River Rch & Prof#=LAURELCK,Main            , 1
Up Type= 0
Dn Type= 1
Dn Known WS=1484.2
DSS Import GetInterval= 0
DSS Import GetPeak= 0
DSS Import FillOption= 0

--- LAURELCK.g01 (geometry) ---

Geom Title=USGS 10m DEM
Program Version=4.10

River Reach=LAURELCK        ,Main
Reach XY= 30
     2028911.731      275543.426     2028282.523      275187.636
     2026459.606      274821.317      2025055.75      275526.769
     2023842.133      275443.049     2023468.287      275640.761
     2022367.135      275144.355     2021833.389      274184.876
     2021569.849      273979.303     2021053.356      274047.879
     2020260.785      273297.252     2019504.745       273297.88
      2018759.72      273560.529     2018090.108      273395.641
     2017827.662      273608.643     2017375.735      273599.979
     2016722.627      274073.921     2015478.703      274472.359
     2014897.191       274436.21     2014513.426      274737.984
     2013539.477      274539.679     2012457.918      274863.701
     2011822.501      275676.201     2011134.133      276177.069
     2010520.499      276165.697     2010018.792      276894.424
     2009200.105      277381.062     2008160.317       277526.14
     2006707.918      277415.785     2005902.361      278648.951

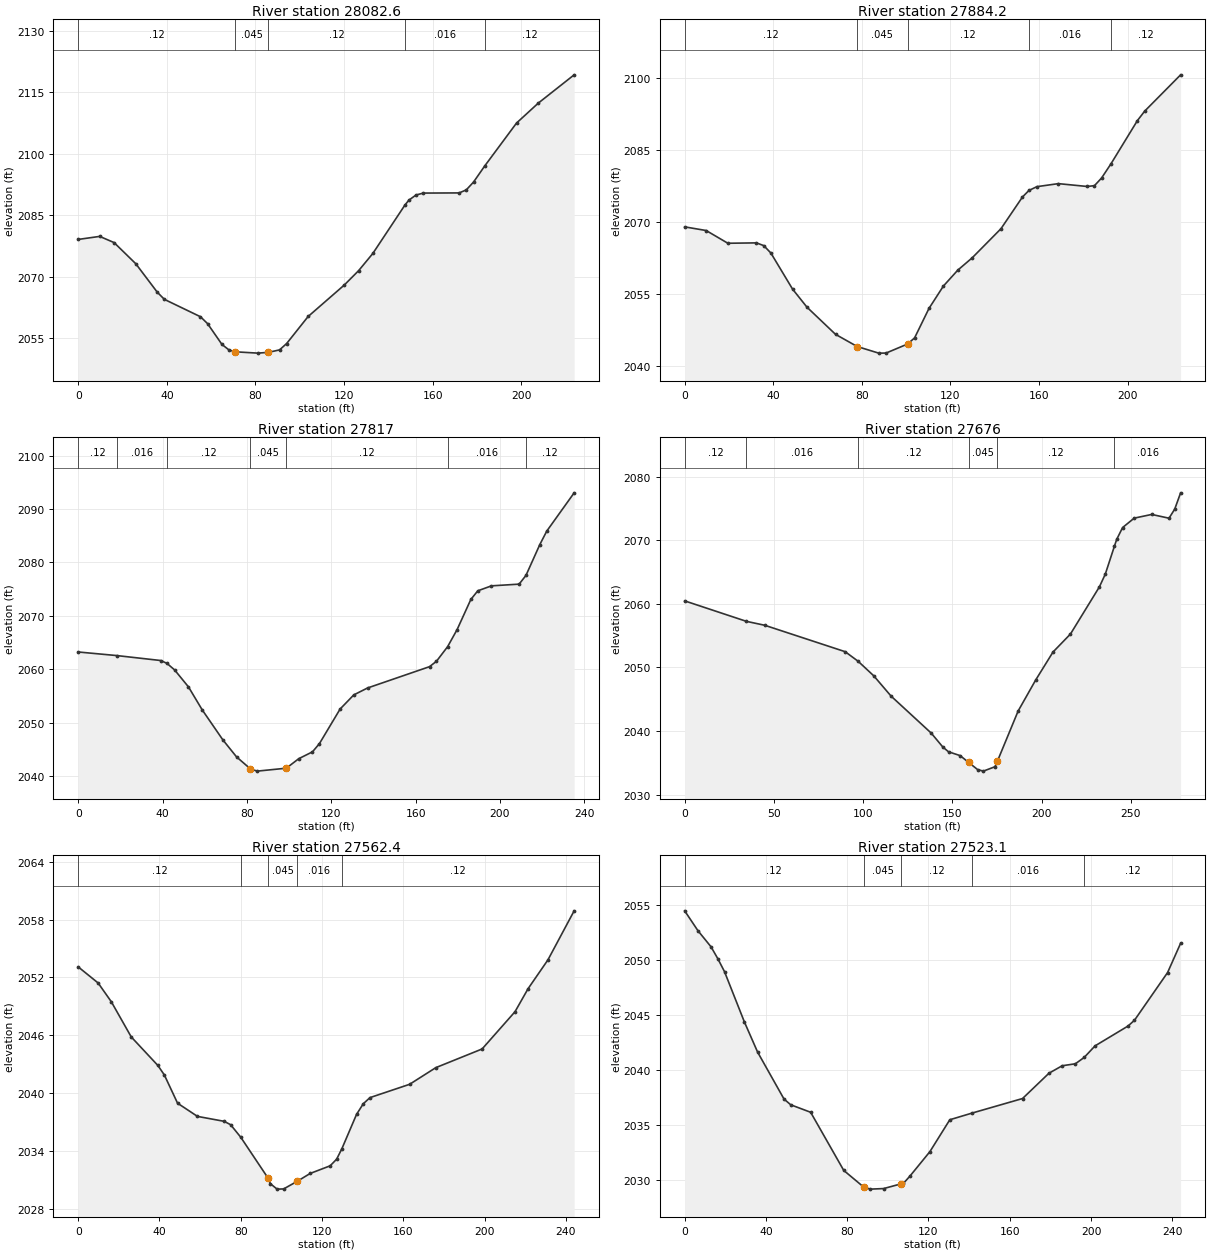
Type RM Length L Ch R = 1 ,28082.6 ,186.7,198.4,209.8
XS GIS Cut Line= 2
     2028872.448      275459.506     2028906.085       275680.86
#Sta/Elev= 30
       0 2079.11     9.7 2079.85    16.2 2078.34      26 2073.18    35.7 2066.24
    38.9  2064.5    55.2 2060.26    58.4 2058.58    64.9 2053.51    68.1 2052.15
    70.9 2051.71    81.1 2051.39    85.9 2051.58    90.9 2052.18    94.1 2053.73
   103.8 2060.32   120.1 2067.98   126.6  2071.5     133 2075.68  147.542087.522
   149.3 2088.69   152.5 2089.94   155.8 2090.41     172 2090.45   175.2 2091.19
   178.5 2093.11  183.512097.012   197.9 2107.49   207.7 2112.34   223.9 2119.24
#Mann= 5 ,-1 , 0
       0     .12       0    70.9    .045       0    85.9     .12       0
  147.54    .016       0  183.51     .12       0
Bank Sta=70.9,85.9
XS Rating Curve= 0 ,0
Exp/Cntr=0.3,0.1

Type RM Length L Ch R = 1 ,27884.2 ,65.7,67.2,68
XS GIS Cut Line= 2
     2028727.049      275413.933     2028647.839      275623.352
#Sta/Elev= 30
       0 2068.97     9.7 2068.21    19.5 2065.56    32.4 2065.64    35.7 2065.07
    38.9 2063.54    48.7 2056.03    55.2 2052.27    68.1 2046.62    77.9 2044.08
    87.6 2042.71    90.9 2042.72   100.6  2044.6   103.8 2045.88   110.3 2052.01
   116.8 2056.66   123.3 2059.97   129.8 2062.53   142.8 2068.59   152.5 2075.18
  155.412076.538     159 2077.33   168.7 2077.96   181.7 2077.37     185 2077.54
   188.2 2079.12  192.422082.055   204.4 2091.08   207.7 2093.05   223.9 2100.59
#Mann= 5 ,-1 , 0
       0     .12       0    77.9    .045       0   100.6     .12       0
  155.41    .016       0  192.42     .12       0
Bank Sta=77.9,100.6
XS Rating Curve= 0 ,0
Exp/Cntr=0.3,0.1

Type RM Length L Ch R = 1 ,27817   ,140.6,141,141.2
XS GIS Cut Line= 2
     2028678.138      275378.891     2028584.822      275594.819
#Sta/Elev= 30
       0 2063.25   18.222062.583    39.2 2061.65    42.12061.114    45.7  2059.9
    52.3 2056.71    58.8 2052.42    68.6  2046.8    75.1 2043.61    81.7 2041.36
    84.9 2040.95    98.7  2041.5   104.6 2043.28   111.1 2044.56   114.4  2046.1
   124.2 2052.57   130.7 2055.22   137.2 2056.51   166.6  2060.5   169.9 2061.51
  175.192064.244   179.7 2067.45   186.2 2073.08   189.5  2074.7     196 2075.63
   209.1 2075.95  212.352077.585   218.9 2083.34   222.2 2085.87   235.2 2093.04
#Mann= 7 ,-1 , 0
       0     .12       0   18.22    .016       0    42.1     .12       0
    81.7    .045       0    98.7     .12       0  175.19    .016       0
  212.35     .12       0
Bank Sta=81.7,98.7
XS Rating Curve= 0 ,0
Exp/Cntr=0.3,0.1

Type RM Length L Ch R = 1 ,27676   ,97.7,113.6,129.4
XS GIS Cut Line= 3
     2028651.094      275360.765     2028523.056      275391.147
     2028463.377       275524.61
#Sta/Elev= 30
       0 2060.45   34.542057.235    44.9 2056.61    89.9 2052.46   97.162050.954
   105.9 2048.67   115.6 2045.48   138.1 2039.66   144.6 2037.47   147.8 2036.72
   154.3 2036.12   159.1 2035.04   164.1 2033.92   167.3 2033.68   173.8 2034.37
  175.14 2035.22   186.8 2043.14   196.6    2048   206.3  2052.4   216.1 2055.24
   232.3 2062.65   235.6 2064.65   240.72069.031     242 2070.12   245.3 2071.98
   251.8 2073.46   261.6 2074.04   271.3 2073.45   274.5 2074.88   277.8 2077.44
#Mann= 6 ,-1 , 0
       0     .12       0   34.54    .016       0   97.16     .12       0
   159.1    .045       0  175.14     .12       0   240.7    .016       0
Bank Sta=159.1,175.14
XS Rating Curve= 0 ,0
Exp/Cntr=0.3,0.1

Type RM Length L Ch R = 1 ,27562.4 ,39.3,39.3,39.3
XS GIS Cut Line= 3
     2028539.249       275286.66     2028401.445      275353.934
     2028378.659      275441.825
#Sta/Elev= 30
       0 2053.09     9.8 2051.42    16.3 2049.47    26.1 2045.82    39.2 2042.86
    42.4 2041.87    48.9 2038.94    58.7 2037.57    71.8 2037.06      75 2036.71
      802035.408   93.39 2031.18    94.6 2030.58    97.9 2030.02   101.1 2030.04
   107.7 2030.82   114.2 2031.65     124 2032.44   127.2 2033.13  129.782034.217
     137 2037.78   140.3 2038.88   143.6 2039.52   163.1  2040.9     176 2042.63
   198.8 2044.57     215 2048.44   221.4 2050.82   231.2 2053.82   244.1 2058.91
#Mann= 5 ,-1 , 0
       0     .12       0      80    .016       0   93.39    .045       0
   107.7    .016       0  129.78     .12       0
Bank Sta=93.39,107.7
XS Rating Curve= 0 ,0
Exp/Cntr=0.3,0.1

Type RM Length L Ch R = 1 ,27523.1 ,159.3,144.1,128.3
XS GIS Cut Line= 3
     2028516.463      275254.108     2028378.659      275321.382
     2028355.873      275409.272
#Sta/Elev= 30
       0  2054.5     6.5  2052.7      13 2051.22    16.3 2050.15    19.6 2048.97
    29.4 2044.39    35.9 2041.65    48.9 2037.38    52.2 2036.86      62 2036.18
    78.3 2030.89    88.1 2029.38    91.4 2029.19    97.9 2029.24   106.7 2029.68
   107.7 2029.72   110.9 2030.38   120.7  2032.6   130.5  2035.5  141.352036.101
   166.3 2037.43   179.3 2039.73   185.8 2040.41   192.3 2040.59  196.622041.164
     202 2042.22   218.2 2044.02   221.4 2044.55   237.7 2048.89   244.1 2051.55
#Mann= 5 ,-1 , 0
       0     .12       0    88.1    .045       0   106.7     .12       0
  141.35    .016       0  196.62     .12       0
Bank Sta=88.1,106.7
XS Rating Curve= 0 ,0
Exp/Cntr=0.3,0.1

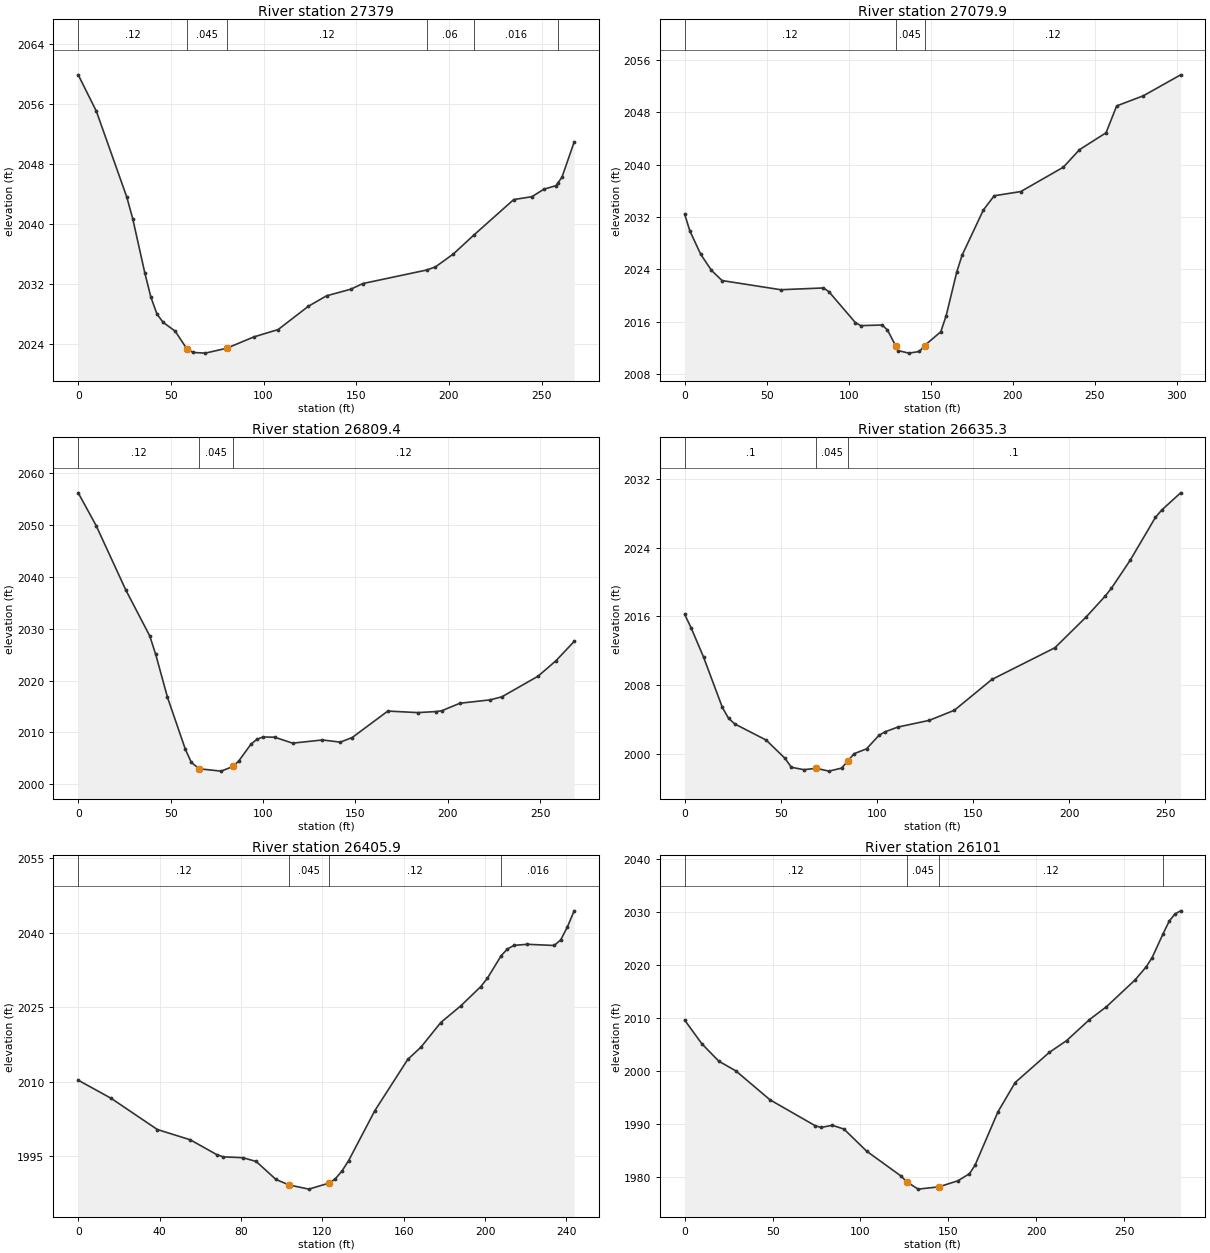
Type RM Length L Ch R = 1 ,27379   ,290.7,299.1,305.3
XS GIS Cut Line= 3
      2028359.21      275142.666     2028297.361       275276.13
     2028299.532      275396.572
#Sta/Elev= 30
       0 2059.84     9.8 2054.99    26.2 2043.58    29.4 2040.71      36 2033.41
    39.2 2030.26    42.5    2028    45.8  2026.9    52.3 2025.73    58.8 2023.31
    62.1 2022.89    68.6  2022.8    80.1 2023.45    94.8 2024.96   107.9 2025.94
   124.2 2029.04     134 2030.43   147.1 2031.31   153.6 2032.06  187.98 2033.86
   192.7 2034.27   202.4 2035.99  213.332038.483     235 2043.24   244.8 2043.62
   251.3 2044.62   257.8 2045.09   258.82045.437     261  2046.2   267.6 2050.89
#Mann= 6 ,-1 , 0
       0     .12       0    58.8    .045       0    80.1     .12       0
  187.98     .06       0  213.33    .016       0   258.8     .12       0
Bank Sta=58.8,80.1
XS Rating Curve= 0 ,0
Exp/Cntr=0.3,0.1

Type RM Length L Ch R = 1 ,27079.9 ,282.6,270.5,256.9
XS GIS Cut Line= 3
     2028145.452      275114.454     2028006.563      275265.279
     2028026.094      275360.765
#Sta/Elev= 30
       0 2032.41     3.2 2029.85     9.8 2026.29    16.3 2023.85    22.8 2022.28
    58.6 2020.88    84.6 2021.15    87.9  2020.6   104.1 2015.86   107.4 2015.39
   120.4 2015.49   123.7 2014.72  128.76 2012.29   130.2 2011.58   136.7 2011.19
   143.2 2011.44   146.3 2012.34   156.2 2014.45   159.5 2016.91     166 2023.63
   169.2 2026.15   182.2 2033.07   188.8 2035.24     205 2035.88     231 2039.61
   240.8 2042.28     257 2044.86   263.5 2048.97   279.8 2050.52   302.5 2053.72
#Mann= 3 ,-1 , 0
       0     .12       0  128.76    .045       0   146.3     .12       0
Bank Sta=128.76,146.3
XS Rating Curve= 0 ,0
Exp/Cntr=0.3,0.1

Type RM Length L Ch R = 1 ,26809.4 ,201.7,174,144.5
XS GIS Cut Line= 3
     2027852.257      274994.177     2027818.685      275168.166
     2027826.576      275258.918
#Sta/Elev= 30
       0 2056.26     9.7 2049.93    25.8 2037.46    38.7 2028.63    41.9 2025.09
    48.3 2016.77      58  2006.7    61.2  2004.2    65.5 2002.97    77.3 2002.52
    83.8 2003.42      87 2004.55    93.4  2007.7    96.6 2008.65    99.9 2009.11
   106.3 2009.07     116 2007.92   132.1 2008.54   141.8 2008.12   148.2    2009
   167.5 2014.12   183.7 2013.82   193.5 2014.02   196.7 2014.18   206.5 2015.63
   222.8 2016.28   229.2 2016.87   248.8 2020.86   258.5 2023.85   268.3 2027.57
#Mann= 3 ,-1 , 0
       0     .12       0    65.5    .045       0    83.8     .12       0
Bank Sta=65.5,83.8
XS Rating Curve= 0 ,0
Exp/Cntr=0.3,0.1

Type RM Length L Ch R = 1 ,26635.3 ,183.4,229.4,274.9
XS GIS Cut Line= 4
     2027667.125      275047.195     2027667.819      275096.153
      2027760.18      275151.362     2027761.569       275252.75
#Sta/Elev= 30
       0 2016.23     3.3 2014.69     9.8 2011.26    19.6 2005.38    22.8 2004.12
    26.1 2003.45    42.4 2001.57    52.2 1999.44    55.5  1998.4      62 1998.12
    68.5 1998.28      75 1997.95    81.6  1998.3    84.8 1999.11    88.1 1999.98
    94.6 2000.55   101.1 2002.13   104.4 2002.55   110.9 2003.09   127.2 2003.87
   140.3 2005.05   159.8 2008.64   192.6 2012.34   208.9 2015.94   218.7 2018.35
     222 2019.28   231.8 2022.56   244.9 2027.55   248.2 2028.41     258 2030.41
#Mann= 3 , 0 , 0
       0      .1       0    68.5    .045       0    84.8      .1       0
Bank Sta=68.5,84.8
XS Rating Curve= 0 ,0
Exp/Cntr=0.3,0.1

Type RM Length L Ch R = 1 ,26405.9 ,330.3,304.9,279.3
XS GIS Cut Line= 3
     2027608.342      275050.435     2027462.943      275153.517
     2027441.242      275215.366
#Sta/Elev= 30
       0  2010.3    16.2 2006.65    38.9 2000.38    55.1 1998.31      68 1995.35
    71.3 1994.88      81 1994.71    87.5 1993.95    97.2 1990.34   103.7 1989.22
   113.4 1988.39   123.5 1989.63   126.4 1990.48   129.6 1991.99   132.9  1994.1
   145.8 2004.16     162 2014.48   168.5 2016.95   178.2 2021.88   188.1 2025.26
   197.9 2029.12   201.2 2030.84  207.95 2035.35     211 2036.69   214.3 2037.42
   220.8 2037.63     234 2037.39   237.2 2038.53   240.5 2041.14   243.8 2044.36
#Mann= 4 ,-1 , 0
       0     .12       0   103.7    .045       0   123.5     .12       0
  207.95    .016       0
Bank Sta=103.7,123.5
XS Rating Curve= 0 ,0
Exp/Cntr=0.3,0.1

Type RM Length L Ch R = 1 ,26101   ,297.8,298.1,296.4
XS GIS Cut Line= 3
     2027302.353      274872.484     2027283.474      274944.359
     2027318.629      275149.176
#Sta/Elev= 30
       0 2009.59     9.7 2005.16    19.4 2001.86    29.1 2000.03    48.5 1994.59
    74.3 1989.69    77.6 1989.38      84 1989.78    90.6 1989.07   103.5 1984.91
     123 1980.24   126.3 1979.14   132.8 1977.76   144.6 1978.19   155.5 1979.34
     162 1980.67   165.2 1982.29   178.2 1992.32     188 1997.84   207.4 2003.51
   217.2 2005.72   230.2 2009.67   239.9 2012.11   256.2 2017.16   262.6 2019.65
   265.9 2021.37   272.12025.836   275.6 2028.23   278.9 2029.58   282.1 2030.17
#Mann= 4 ,-1 , 0
       0     .12       0   126.3    .045       0   144.6     .12       0
   272.1    .016       0
Bank Sta=126.3,144.6
XS Rating Curve= 0 ,0
Exp/Cntr=0.3,0.1

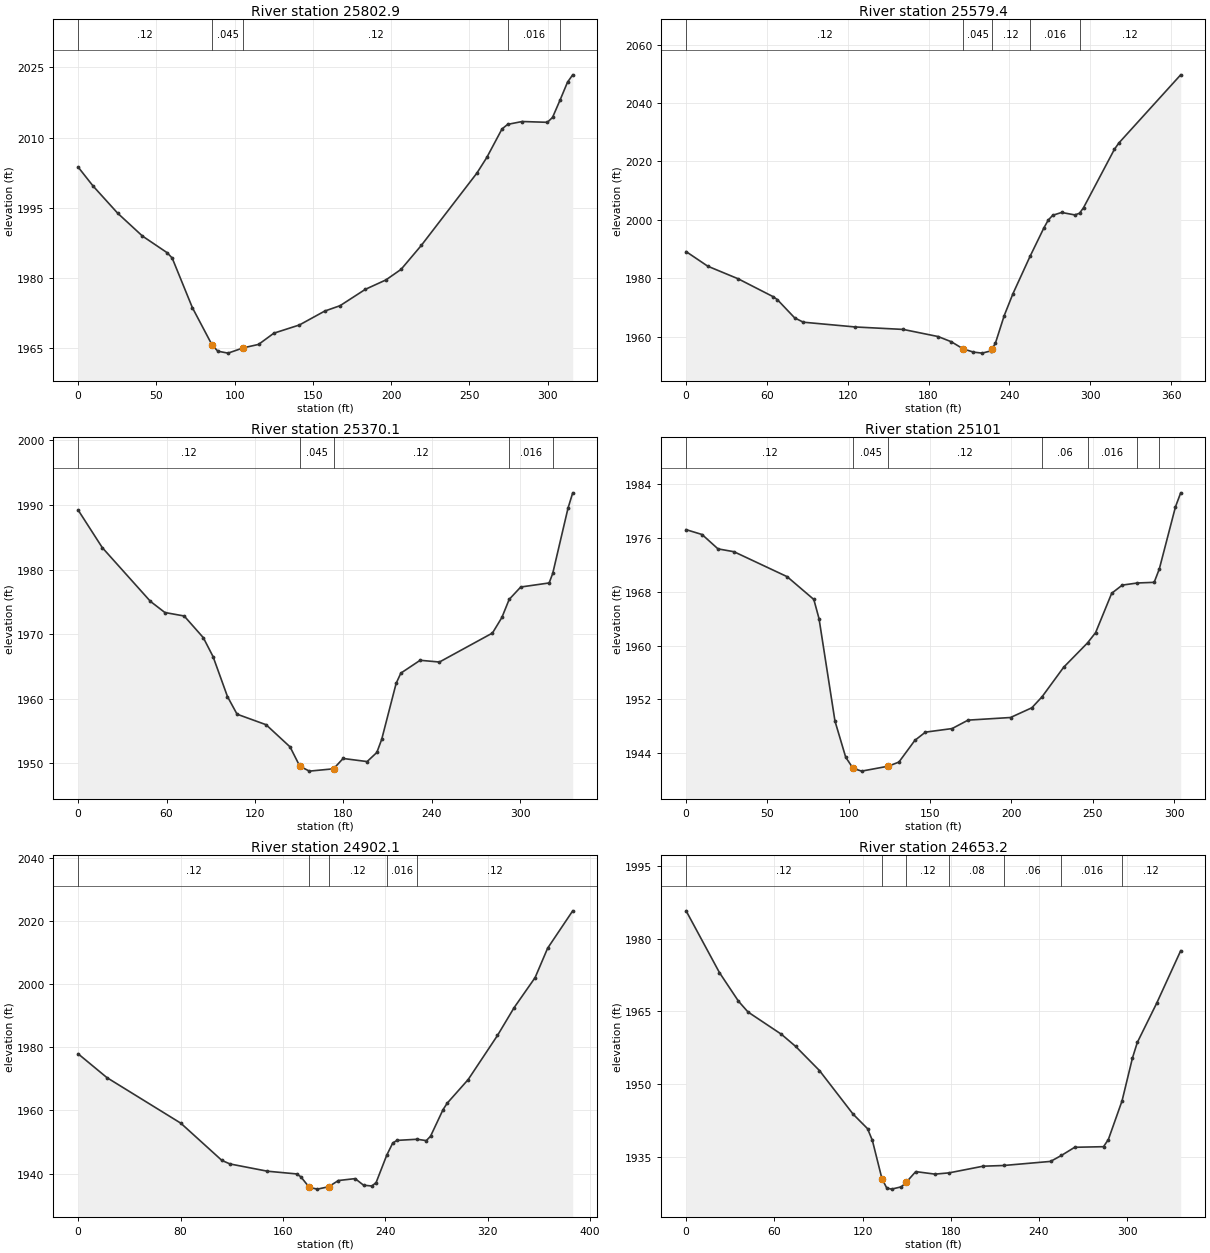
Type RM Length L Ch R = 1 ,25802.9 ,219,223.4,227.1
XS GIS Cut Line= 4
     2027049.532      274832.336      2027025.66       274890.93
     2027049.532      275025.479     2027046.276      275141.581
#Sta/Elev= 30
       0 2003.69     9.5 1999.66    25.3 1993.83    41.1 1988.96    56.9  1985.4
    60.1 1984.27      73 1973.68    85.6  1965.7    89.3 1964.37    95.8 1963.96
   105.6 1965.09   115.3 1965.82   125.1 1968.22   141.4 1969.97   157.6 1972.94
   167.4 1974.09   183.6 1977.59   196.7 1979.59   206.4 1981.85   219.3 1986.95
   254.8 2002.38   261.2 2005.75   270.9 2011.83  274.53 2012.81   283.8 2013.42
   299.9 2013.25   303.2 2014.29  308.122018.087   312.8 2021.84   316.1 2023.39
#Mann= 5 ,-1 , 0
       0     .12       0    85.6    .045       0   105.6     .12       0
  274.53    .016       0  308.12     .12       0
Bank Sta=85.6,105.6
XS Rating Curve= 0 ,0
Exp/Cntr=0.3,0.1

Type RM Length L Ch R = 1 ,25579.4 ,194.7,209.3,223.3
XS GIS Cut Line= 3
     2026921.493      274824.741     2026839.028      274985.331
     2026840.113      275171.963
#Sta/Elev= 30
       0 1989.11    16.1  1984.1    38.7 1979.78    64.5 1973.69    67.7 1972.67
    80.6  1966.4      87 1964.92   125.7 1963.28   161.2 1962.44   187.1    1960
   196.9 1958.22   205.6  1955.8   213.3 1954.67   219.8 1954.32   226.4 1955.11
  227.27  1955.9   229.6 1957.67   236.2 1967.21   242.7 1974.73   255.41987.523
   265.7 1997.29   268.9 1999.93   272.2 2001.55   278.8 2002.52   288.6 2001.68
  292.08 2002.24   295.1 2004.18     318 2024.17   321.3 2026.32   367.2 2049.68
#Mann= 5 ,-1 , 0
       0     .12       0   205.6    .045       0  227.27     .12       0
   255.4    .016       0  292.08     .12       0
Bank Sta=205.6,227.27
XS Rating Curve= 0 ,0
Exp/Cntr=0.3,0.1

Type RM Length L Ch R = 1 ,25370.1 ,289.1,269.1,248.7
XS GIS Cut Line= 3
     2026777.179      274760.722     2026612.249      274988.586
     2026606.823       275042.84
#Sta/Elev= 30
       0 1989.22    16.4  1983.4    49.1 1975.07    58.9 1973.35      72 1972.81
      85 1969.45    91.6 1966.52   101.4 1960.32   107.9  1957.6   127.6 1955.97
   143.9 1952.53   150.5 1949.54     157 1948.78   173.4 1949.14   179.9 1950.74
   196.2 1950.26   202.8 1951.67   206.1  1953.7   215.9 1962.37   219.1 1963.96
   232.2 1965.95   245.3 1965.68   281.3 1970.17   287.7 1972.58  292.661975.383
   300.5  1977.3   319.8 1977.93  322.231979.411   332.6 1989.51   335.8 1991.89
#Mann= 5 ,-1 , 0
       0     .12       0   150.5    .045       0   173.4     .12       0
  292.66    .016       0  322.23     .12       0
Bank Sta=150.5,173.4
XS Rating Curve= 0 ,0
Exp/Cntr=0.3,0.1

Type RM Length L Ch R = 1 ,25101   ,200.3,198.9,197.3
XS GIS Cut Line= 2
     2026404.964      274720.588     2026486.417      275013.529
#Sta/Elev= 30
       0 1977.18     9.8 1976.46    19.6 1974.33    29.4 1973.91    62.1 1970.21
    78.5 1966.83    81.7 1963.99    91.5  1948.8    98.1 1943.44   102.6  1941.8
   107.9 1941.38   124.2 1942.11   130.8 1942.72   140.6 1945.94   147.1 1947.16
   163.5 1947.69   173.3 1948.94   199.4 1949.33   212.5 1950.77  218.791952.402
   232.1 1956.79  246.751960.395   251.7 1961.91   261.6 1967.75   268.1 1968.96
  277.411969.274   287.7 1969.37  290.871971.358   300.8 1980.57     304 1982.64
#Mann= 7 ,-1 , 0
       0     .12       0   102.6    .045       0   124.2     .12       0
  218.79     .06       0  246.75    .016       0  277.41     .06       0
  290.87    .016       0
Bank Sta=102.6,124.2
XS Rating Curve= 0 ,0
Exp/Cntr=0.3,0.1

Type RM Length L Ch R = 1 ,24902.1 ,255.5,248.9,240.3
XS GIS Cut Line= 3
      2026246.58       274730.34      2026240.07      274868.143
     2026322.535      275102.518
#Sta/Elev= 30
       0 1977.94    22.5  1970.4    80.2 1955.97   112.3 1944.17   118.7 1943.05
   147.8 1940.76   170.6  1939.9   173.9 1939.02   180.7  1935.6     187 1935.08
   195.7 1935.84   203.3  1937.8   216.4 1938.41     223 1936.32   229.5 1936.07
   232.8 1937.17  241.09 1945.82   245.8  1949.7   249.1 1950.52  264.861950.878
     272 1950.45   275.3 1951.82   285.1 1960.27   288.3 1962.29   304.7 1969.78
   327.6 1983.75   340.6 1992.56     357 2002.08   366.8  2011.4   386.4 2023.24
#Mann= 5 ,-1 , 0
       0     .12       0   180.7    .045       0   195.7     .12       0
  241.09    .016       0  264.86     .12       0
Bank Sta=180.7,195.7
XS Rating Curve= 0 ,0
Exp/Cntr=0.3,0.1

Type RM Length L Ch R = 1 ,24653.2 ,223.4,226.7,227.6
XS GIS Cut Line= 3
     2025974.662       274797.31     2025985.513      274890.626
     2026131.997      275083.768
#Sta/Elev= 30
       0  1985.8    22.7 1973.02    35.6 1967.13    42.1 1964.89    64.8 1960.29
    74.5 1957.78    90.7 1952.79   113.6 1943.77   123.4 1940.78   126.7 1938.34
   133.2 1930.44   136.5 1928.49   139.8 1928.28   146.4 1928.76   149.6 1929.66
   156.2  1931.9   169.3 1931.38   178.91931.643     202 1933.02  215.971933.164
   247.9 1934.01  255.321935.248   264.3 1936.93   283.9 1937.05   287.2 1938.53
   296.51946.508   303.6 1955.39   306.9  1958.6     320 1966.66   336.4 1977.55
#Mann= 7 ,-1 , 0
       0     .12       0   133.2    .045       0   149.6     .12       0
   178.9     .08       0  215.97     .06       0  255.32    .016       0
   296.5     .12       0
Bank Sta=133.2,149.6
XS Rating Curve= 0 ,0
Exp/Cntr=0.3,0.1

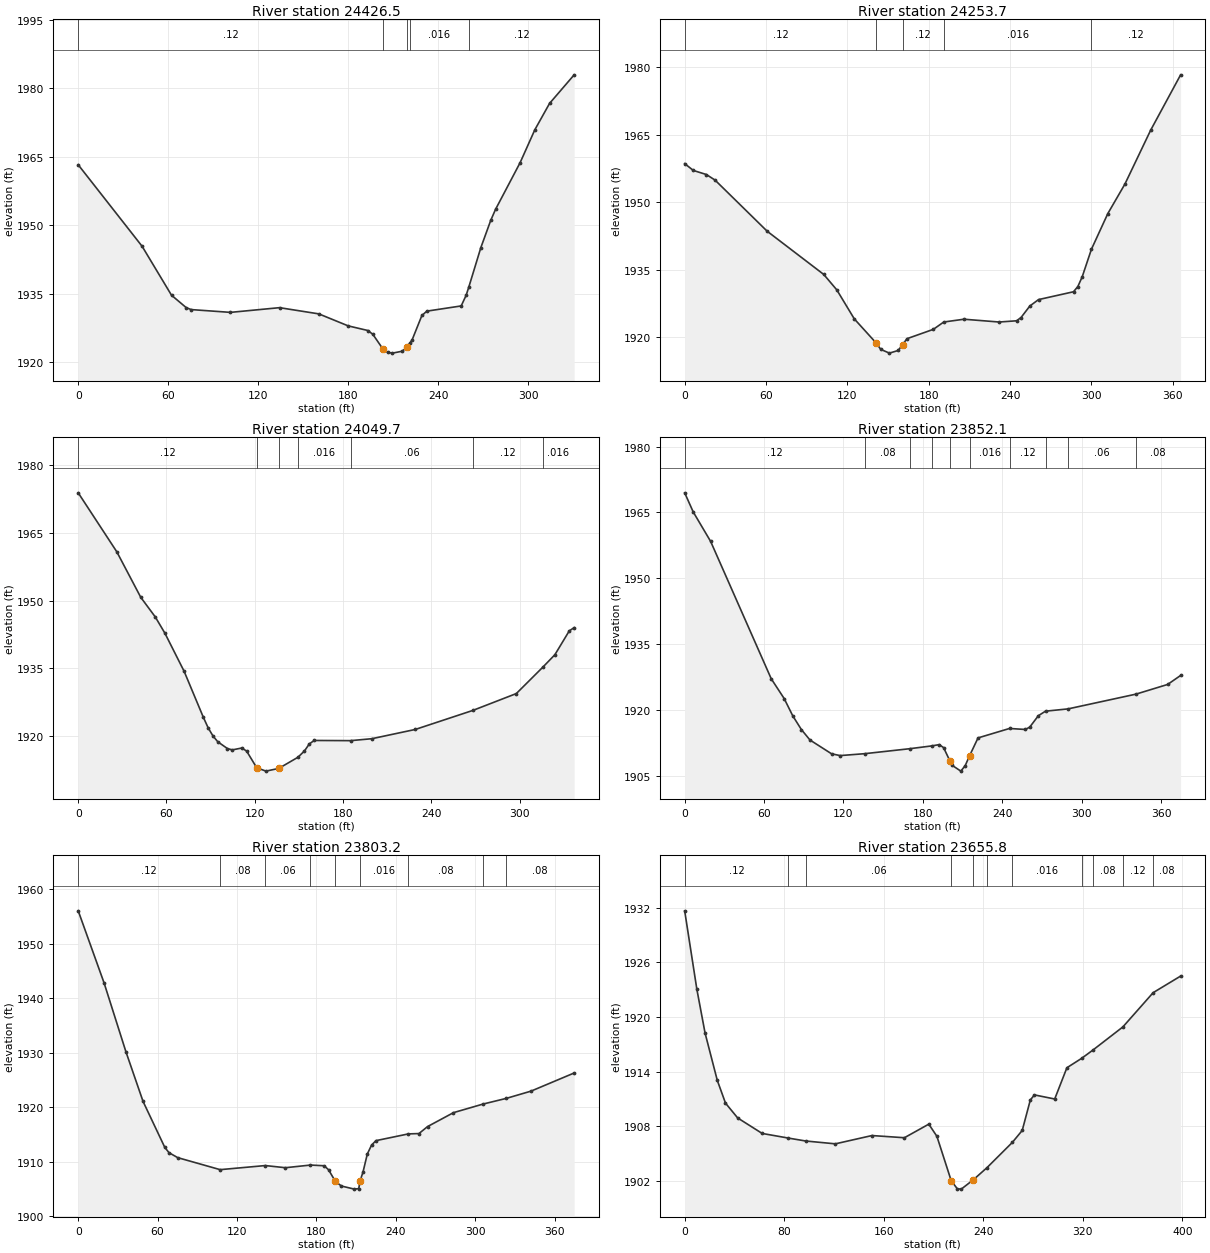
Type RM Length L Ch R = 1 ,24426.5 ,167.3,172.8,180.2
XS GIS Cut Line= 2
     2025812.209      274933.274     2026009.775      275198.352
#Sta/Elev= 30
       0 1963.25    42.6 1945.41    62.2  1934.7      72 1931.99    75.3 1931.56
   101.5 1930.95   134.2 1931.98   160.4 1930.62     180 1927.99   193.1 1926.98
   196.4 1926.15   202.9 1923.04   206.2 1922.21   209.5 1922.03     216 1922.45
   218.9 1923.28  221.261924.315   222.6 1924.94   229.1 1930.27   232.4 1931.22
   255.3 1932.36   258.6 1934.69  260.391936.502   268.4 1945.12     275 1951.09
   278.2  1953.5   294.6 1963.73   304.4 1970.92   314.2 1976.68   330.6 1982.94
#Mann= 5 ,-1 , 0
       0     .12       0   202.9    .045       0   218.9     .12       0
  221.26    .016       0  260.39     .12       0
Bank Sta=202.9,218.9
XS Rating Curve= 0 ,0
Exp/Cntr=0.3,0.1

Type RM Length L Ch R = 1 ,24253.7 ,213.6,204,193.8
XS GIS Cut Line= 4
     2025697.535      275018.968     2025764.809      275104.689
     2025815.808      275271.789     2025872.231      275331.468
#Sta/Elev= 30
       0 1958.54     6.4 1957.02      16 1956.12    22.4 1954.88    60.9 1943.51
   102.6 1933.92   112.2  1930.5   125.1 1924.06   141.3 1918.68   144.6 1917.29
     151 1916.45   157.5 1917.04   160.7 1918.35     164 1919.66   183.4 1921.73
  191.09 1923.36     206 1923.98   231.9 1923.36   244.8 1923.63   248.1 1924.36
   254.6 1926.92     261 1928.34   286.8 1930.08     290 1931.24   293.2 1933.39
  300.031939.532   312.1 1947.44   324.7 1953.99   343.7 1965.96   365.8 1978.26
#Mann= 5 ,-1 , 0
       0     .12       0   141.3    .045       0   160.7     .12       0
  191.09    .016       0  300.03     .12       0
Bank Sta=141.3,160.7
XS Rating Curve= 0 ,0
Exp/Cntr=0.3,0.1

Type RM Length L Ch R = 1 ,24049.7 ,192.6,197.7,201.8
XS GIS Cut Line= 2
     2025515.143      275142.409     2025739.953      275393.574
#Sta/Elev= 30
       0 1973.89    26.2 1960.83    42.5 1950.73    52.4 1946.36    58.9 1942.78
      72 1934.31    85.1 1924.08    88.4 1921.73    91.6 1919.98    94.9 1918.68
   101.4 1917.19   104.7 1916.89   111.3 1917.31   114.5 1916.61   121.3 1912.94
   127.6 1912.18   136.3 1912.78  149.34 1915.25   153.8 1916.66   157.1 1918.22
   160.4 1918.98  185.211918.938   199.6 1919.37   229.1 1921.42  268.271925.645
   297.8 1929.38  315.611935.166     324 1937.99   333.8 1943.29   337.1    1944
#Mann= 7 ,-1 , 0
       0     .12       0   121.3    .045       0   136.3     .08       0
  149.34    .016       0  185.21     .06       0  268.27     .12       0
  315.61    .016       0
Bank Sta=121.3,136.3
XS Rating Curve= 0 ,0
Exp/Cntr=0.3,0.1

Type RM Length L Ch R = 1 ,23852.1 ,49.3,48.9,48.3
XS GIS Cut Line= 3
      2025390.46      275183.899     2025398.056      275268.534
     2025543.455      275519.185
#Sta/Elev= 30
       0 1969.48     6.5  1965.1    19.6 1958.42    65.4 1927.12    75.2  1922.6
    81.7 1918.66    88.2 1915.54    94.7 1913.16     111 1910.02   117.5 1909.61
   136.11910.047  170.251911.184  186.611911.812   192.4 1912.11   195.7 1911.41
   200.3 1908.48   202.2 1907.38   208.7 1906.07     212 1907.32   215.3 1909.57
   221.7 1913.64  245.481915.789   257.5 1915.56   260.8 1916.11   267.3  1918.7
  272.69 1919.73  289.691920.248  340.991923.607     365 1925.82   374.8 1927.87
#Mann= 10 ,-1 , 0
       0     .12       0   136.1     .08       0  170.25     .06       0
  186.61     .08       0   200.3    .045       0   215.3    .016       0
  245.48     .12       0  272.69     .08       0  289.69     .06       0
  340.99     .08       0
Bank Sta=200.3,215.3
XS Rating Curve= 0 ,0
Exp/Cntr=0.3,0.1

Type RM Length L Ch R = 1 ,23803.2 ,149.1,147.4,145.4
XS GIS Cut Line= 3
     2025349.228      275208.855     2025356.823      275293.491
     2025502.223      275544.142
#Sta/Elev= 30
       0 1956.04    19.6 1942.77      36 1930.21      49 1921.05    65.4 1912.63
    68.6 1911.64    75.2 1910.73  107.251908.525  141.391909.277   156.6 1908.88
  175.541909.369   185.9 1909.24   189.2  1908.5   194.3 1906.39   198.9 1905.52
   208.7 1904.95     212 1905.05  213.07  1906.5   215.2 1908.06   218.5 1911.41
   221.7 1913.03     225 1913.85  249.551915.089   257.5 1915.15     264 1916.43
   283.6 1918.99  305.85 1920.56  323.641921.617   342.2 1922.94   374.8 1926.27
#Mann= 9 ,-1 , 0
       0     .12       0  107.25     .08       0  141.39     .06       0
  175.54     .08       0   194.3    .045       0  213.07    .016       0
  249.55     .08       0  305.85     .06       0  323.64     .08       0
Bank Sta=194.3,213.07
XS Rating Curve= 0 ,0
Exp/Cntr=0.3,0.1

Type RM Length L Ch R = 1 ,23655.8 ,162.3,162.6,162.7
XS GIS Cut Line= 3
     2025180.091      275220.253     2025181.042      275292.406
     2025372.014      275557.163
#Sta/Elev= 30
       0 1931.66     9.8 1923.04    16.4 1918.24    26.2 1913.06    32.8 1910.56
    42.6 1908.93    62.3 1907.23   83.381906.721   97.241906.402   121.1 1906.09
   150.5    1907   176.6 1906.76   196.2 1908.25   202.7 1906.92   214.2 1902.05
   219.1 1901.16   222.3 1901.12   232.1 1902.16  242.93 1903.47  263.44 1906.26
   271.3 1907.56   277.8  1910.9   281.1 1911.46   297.4 1911.01   307.2 1914.44
  319.121915.478  328.321916.402  352.19 1918.92  376.521922.679   398.6  1924.5
#Mann= 11 ,-1 , 0
       0     .12       0   83.38     .08       0   97.24     .06       0
   214.2    .045       0   232.1     .06       0  242.93     .08       0
  263.44    .016       0  319.12     .12       0  328.32     .08       0
  352.19     .12       0  376.52     .08       0
Bank Sta=214.2,232.1
XS Rating Curve= 0 ,0
Exp/Cntr=0.3,0.1

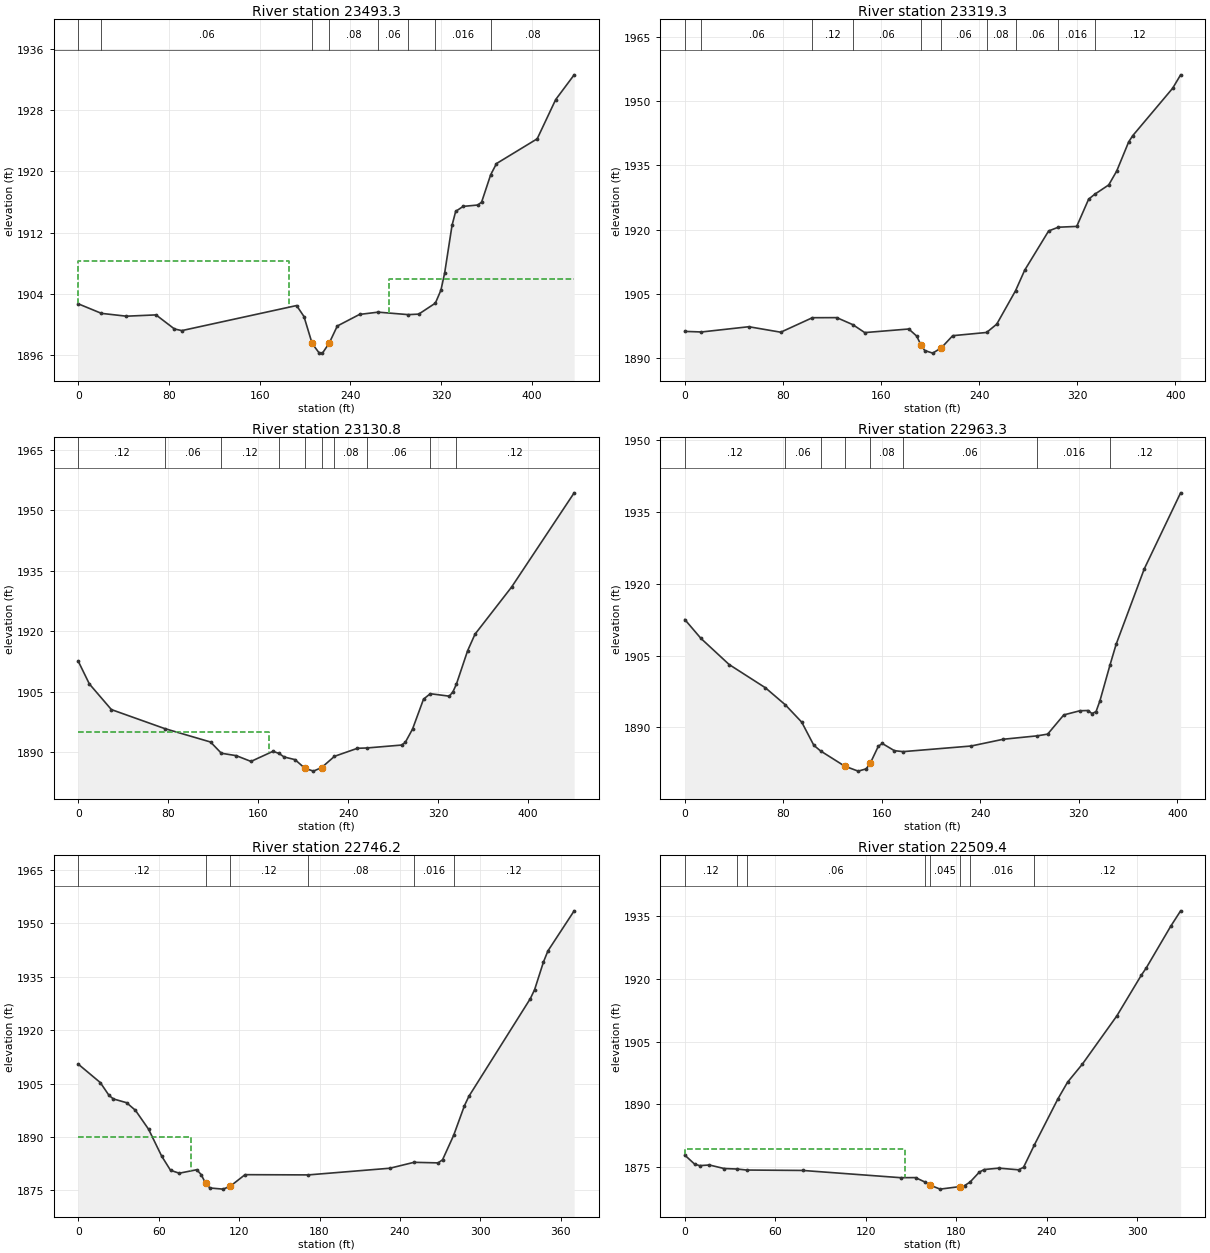
Type RM Length L Ch R = 1 ,23493.3 ,160.7,173.9,186.7
XS GIS Cut Line= 3
     2025057.344      275292.406     2025063.855      275403.083
     2025254.827       275667.84
#Sta/Elev= 30
       0 1902.71   20.38 1901.47    42.4  1901.1    68.5 1901.27    84.8 1899.43
    91.3 1899.22   192.5 1902.49     199 1901.06   206.2 1897.54   212.1 1896.36
   215.3 1896.28   221.2 1897.57   228.4 1899.82     248 1901.33   264.41901.629
  290.851901.305   300.2 1901.37  314.891902.803   319.8  1904.5   323.1 1906.75
   329.6 1912.96   332.8 1914.78   339.4 1915.43   352.4 1915.61   355.7    1916
  363.691919.565   368.8 1921.02   404.7 1924.25     421 1929.37   437.3  1932.6
#Mann= 8 ,-1 , 0
       0     .12       0   20.38     .06       0   206.2    .045       0
   221.2     .08       0   264.4     .06       0  290.85     .08       0
  314.89    .016       0  363.69     .08       0
#XS Ineff= 2 , 0
          185.37 1908.35  274.15          1905.9
Permanent Ineff=
       F       F
Bank Sta=206.2,221.2
XS Rating Curve= 0 ,0
Exp/Cntr=0.3,0.1

Type RM Length L Ch R = 1 ,23319.3 ,191,188.5,187
XS GIS Cut Line= 2
     2024951.007      275333.638     2024972.709      275737.284
#Sta/Elev= 30
       0 1896.25    13.61896.115    52.2 1897.34    78.2 1896.06  104.021899.444
   123.9 1899.46  136.971897.822   146.7 1895.97   182.6 1896.81   189.1 1895.14
   192.3 1893.19   195.6 1891.79   202.1 1891.18  209.121892.414   218.4 1895.25
  246.031895.999   254.3 1897.94  269.661905.757   277.1 1910.54   296.6 1919.68
  304.46 1920.55   319.5 1920.74   329.2 1927.09  334.041928.211   345.6 1930.42
   352.1 1933.66   361.8 1940.42   365.1 1941.89   397.7 1952.97   404.2  1956.1
#Mann= 10 ,-1 , 0
       0     .08       0    13.6     .06       0  104.02     .12       0
  136.97     .06       0   192.3    .045       0  209.12     .06       0
  246.03     .08       0  269.66     .06       0  304.46    .016       0
  334.04     .12       0
Bank Sta=192.3,209.12
XS Rating Curve= 0 ,0
Exp/Cntr=0.3,0.1

Type RM Length L Ch R = 1 ,23130.8 ,162.8,167.5,169.8
XS GIS Cut Line= 2
     2024770.886      275324.958     2024792.587      275765.496
#Sta/Elev= 30
       0 1912.54     9.8 1906.94    29.4 1900.57   76.881895.849   117.6 1892.52
  127.241889.729   140.5 1889.13   153.6  1887.7   173.2 1890.21  178.551889.679
     183 1888.81   192.8 1888.14   201.4 1886.03   209.1 1885.29   216.4 1886.16
  227.85 1888.96   248.3 1890.96  256.691891.039   287.5 1891.76   290.8  1892.4
   297.3 1895.72   307.1 1903.16  313.081904.511     330  1903.9   333.2 1904.95
  336.341906.882   346.3 1915.17   352.9 1919.29   385.5 1931.01   441.1 1954.38
#Mann= 10 ,-1 , 0
       0     .12       0   76.88     .06       0  127.24     .12       0
  178.55     .06       0   201.4    .045       0   216.4     .06       0
  227.85     .08       0  256.69     .06       0  313.08    .016       0
  336.34     .12       0
#XS Ineff= 2 , 0
          169.74 1895.08
Permanent Ineff=
       F       F
Bank Sta=201.4,216.4
XS Rating Curve= 0 ,0
Exp/Cntr=0.3,0.1

Type RM Length L Ch R = 1 ,22963.3 ,215.9,217.1,218.3
XS GIS Cut Line= 2
     2024639.809      275351.433     2024634.518      275754.108
#Sta/Elev= 30
       0 1912.53    13.1 1908.59      36 1903.14    65.5 1898.28   81.72 1894.71
      95  1891.1   104.8 1886.28  110.231885.113   129.8 1881.94   140.8 1880.89
   147.3 1881.36   150.6 1882.52   157.2 1886.09   160.4 1886.66   170.2 1885.16
  177.311884.959   232.5 1886.13   258.6 1887.54  286.251888.256   294.7 1888.61
   307.8 1892.62   320.9 1893.49   327.4 1893.54   330.7 1892.91     334 1893.31
   337.2  1895.6  345.331903.029   350.3 1907.35   373.2 1923.12   402.7 1938.97
#Mann= 8 ,-1 , 0
       0     .12       0   81.72     .06       0  110.23     .12       0
   129.8    .045       0   150.6     .08       0  177.31     .06       0
  286.25    .016       0  345.33     .12       0
Bank Sta=129.8,150.6
XS Rating Curve= 0 ,0
Exp/Cntr=0.3,0.1

Type RM Length L Ch R = 1 ,22746.2 ,236.3,236.8,236.4
XS GIS Cut Line= 2
     2024430.174      275387.892     2024401.962      275756.815
#Sta/Elev= 30
       0 1910.46    16.4  1905.3    22.9  1901.7    26.2  1900.7      36 1899.65
    42.6 1897.52    52.4 1892.21    62.2 1884.64    68.8 1880.67    75.3 1879.85
    88.4 1880.83    91.7 1879.43      95 1877.01    98.2  1875.7     108 1875.38
   113.3 1876.17   124.4 1879.44  171.581879.374   232.5 1881.25  250.491882.909
   268.5 1882.75   271.8 1883.63  280.11 1890.52   288.1 1898.79   291.4 1901.42
   337.3 1928.88   340.5 1931.41   347.1 1939.17   350.4 1942.26     370 1953.53
#Mann= 6 ,-1 , 0
       0     .12       0      95    .045       0   113.3     .12       0
  171.58     .08       0  250.49    .016       0  280.11     .12       0
#XS Ineff= 2 , 0
           84.09 1890.06
Permanent Ineff=
       F       F
Bank Sta=95,113.3
XS Rating Curve= 0 ,0
Exp/Cntr=0.3,0.1

Type RM Length L Ch R = 1 ,22509.4 ,369.4,365.7,362.2
XS GIS Cut Line= 2
      2024210.99      275390.062     2024187.118      275717.753
#Sta/Elev= 30
       0 1877.89     6.5 1875.74     9.8 1875.38    16.3 1875.53      26 1874.69
   34.771874.566   40.931874.327    78.1 1874.23   143.1  1872.5   152.9 1872.52
   159.4 1871.42   162.8 1870.69   169.2 1869.77   182.2 1870.37   185.4 1870.61
  189.011871.439   195.2 1873.83   198.4 1874.45   208.2 1874.78   221.2 1874.38
   224.5 1874.98  231.681880.324   247.2 1891.26   253.7 1895.31   263.5 1899.61
   286.3  1911.1   302.5  1920.8   305.8 1922.55     322 1932.49   328.6 1936.19
#Mann= 8 ,-1 , 0
       0     .12       0   34.77     .08       0   40.93     .06       0
   159.4     .08       0   162.8    .045       0   182.2     .08       0
  189.01    .016       0  231.68     .12       0
#XS Ineff= 2 , 0
          145.67 1879.26
Permanent Ineff=
       F       F
Bank Sta=162.8,182.2
XS Rating Curve= 0 ,0
Exp/Cntr=0.3,0.1