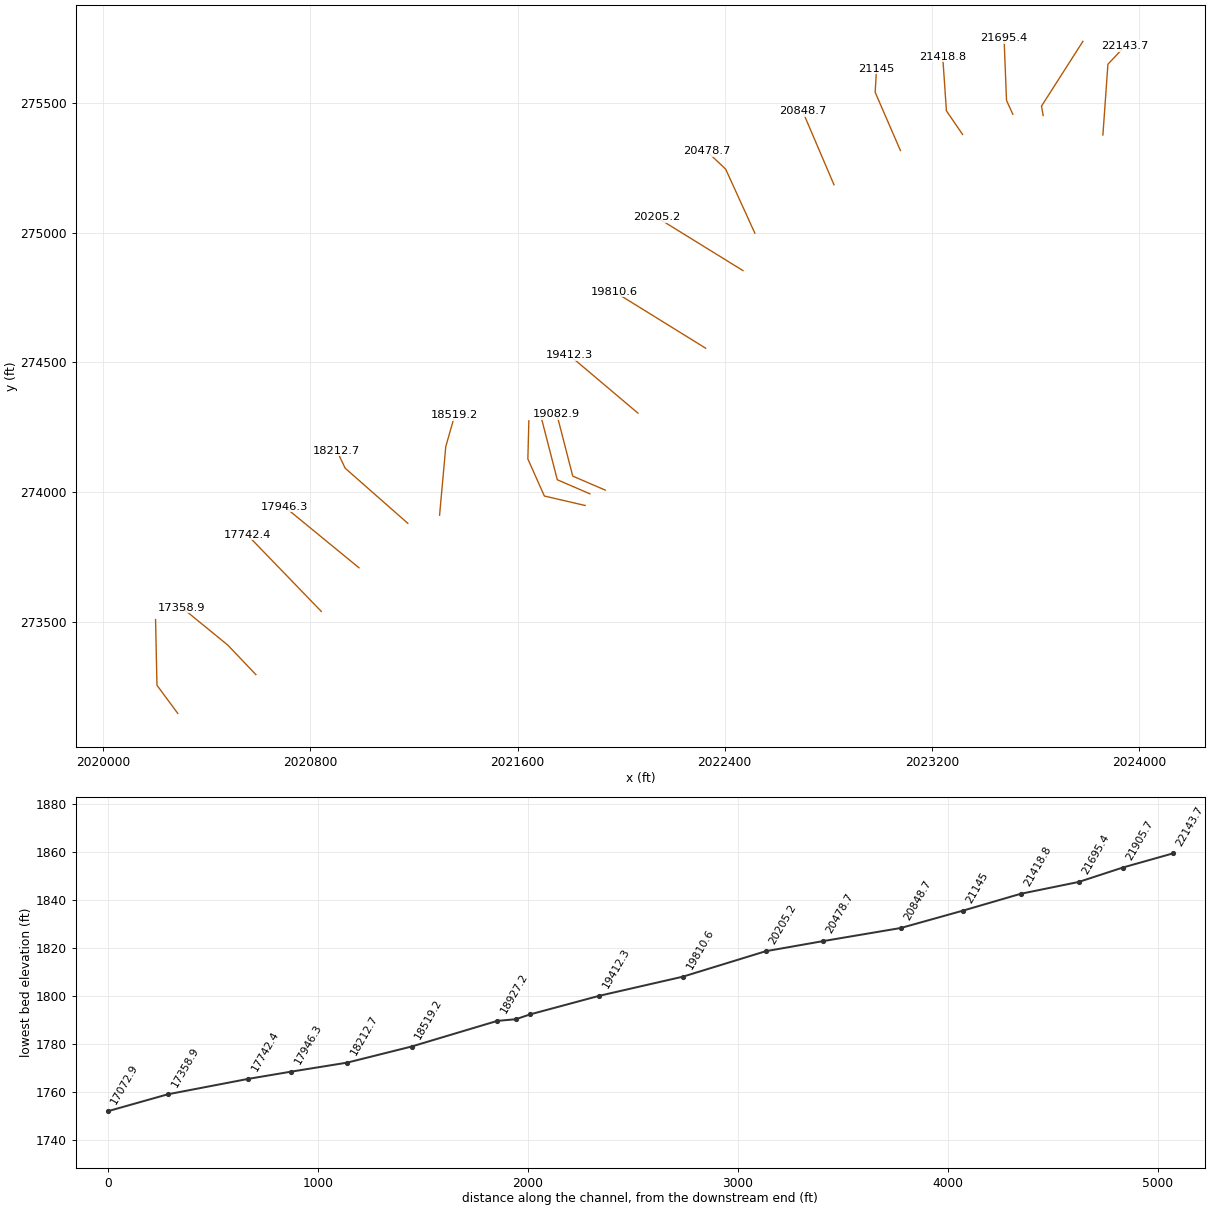
HEC-RAS study LAURELCK.prj: LAURELCK

--- LAURELCK.g01 (geometry) --- (continued)

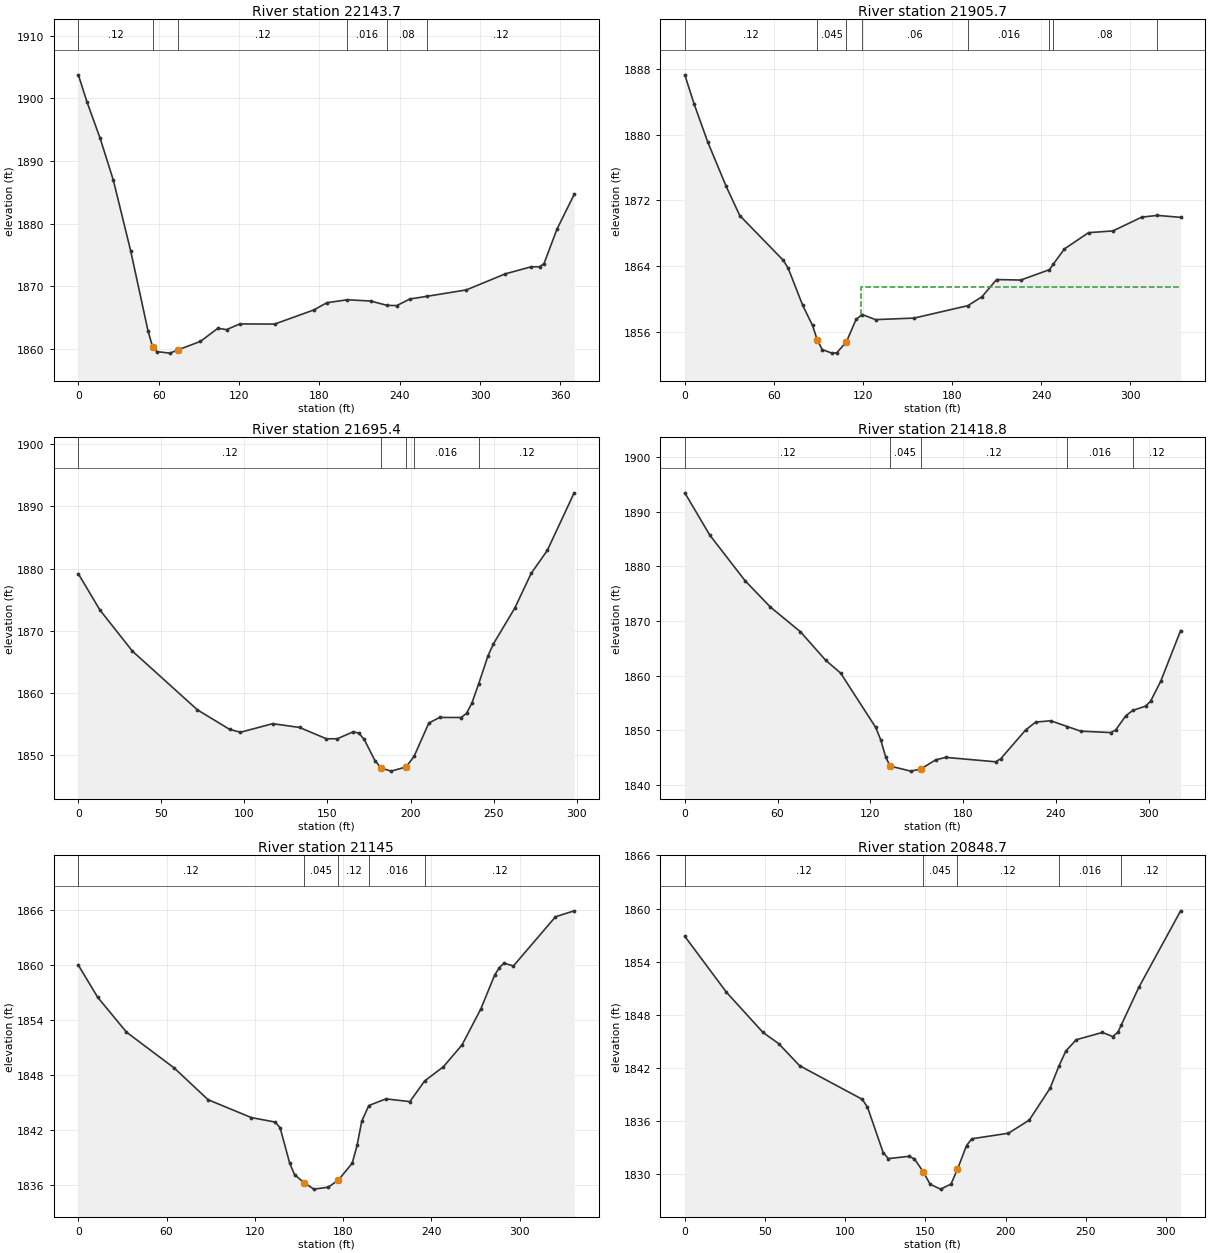
Type RM Length L Ch R = 1 ,22143.7 ,249.2,238,226.7
XS GIS Cut Line= 3
      2023860.78      275378.229     2023880.088      275651.144
     2023946.393      275721.419
#Sta/Elev= 30
       0 1903.75     6.5  1899.4    16.3  1893.6    26.1 1886.96    39.1 1875.63
    52.1 1862.81    55.4 1860.35    58.6 1859.56    68.4 1859.32    74.1 1859.81
    91.2  1861.2   104.2 1863.29   110.7 1863.07   120.5 1863.98   146.6 1863.96
   175.9 1866.22   185.6 1867.37  200.841867.837   218.2 1867.64  230.451866.946
   237.8 1866.91   247.5 1867.96  260.061868.384   289.7 1869.41   318.7 1871.97
     338  1873.1   344.4 1873.11   347.7 1873.62   357.3 1879.08   370.2 1884.65
#Mann= 6 ,-1 , 0
       0     .12       0    55.4    .045       0    74.1     .12       0
  200.84    .016       0  230.45     .08       0  260.06     .12       0
Bank Sta=55.4,74.1
XS Rating Curve= 0 ,0
Exp/Cntr=0.3,0.1

Type RM Length L Ch R = 1 ,21905.7 ,196.3,210.3,223.9
XS GIS Cut Line= 3
     2023630.044      275452.996     2023623.533      275489.454
     2023783.473      275739.454
#Sta/Elev= 30
       0 1887.27     6.2 1883.77    15.4 1879.13    27.8 1873.74      37 1870.17
    66.4 1864.71    69.6 1863.77    79.4 1859.25      86 1856.81    89.2 1855.05
    92.5 1853.89      99 1853.45   102.3 1853.49   108.8 1854.82   115.3 1857.55
  119.441858.143   128.4 1857.52   154.4 1857.71  190.651859.224   200.1 1860.31
   209.9 1862.39   226.2 1862.33  245.461863.591  248.011864.252   255.6 1866.12
   271.8 1868.09   288.2  1868.3   307.7 1869.98  318.151870.186   333.8 1869.95
#Mann= 8 ,-1 , 0
       0     .12       0    89.2    .045       0   108.8     .12       0
  119.44     .06       0  190.65    .016       0  245.46     .06       0
  248.01     .08       0  318.15     .12       0
#XS Ineff= 2 , 0
                          118.82         1861.52
Permanent Ineff=
       F       F
Bank Sta=89.2,108.8
XS Rating Curve= 0 ,0
Exp/Cntr=0.3,0.1

Type RM Length L Ch R = 1 ,21695.4 ,276,276.6,275.6
XS GIS Cut Line= 3
     2023512.856      275458.204     2023488.456      275511.602
     2023479.002      275751.173
#Sta/Elev= 30
       0 1879.17      13 1873.34    32.6 1866.72    71.7 1857.29    91.1 1854.15
    97.6 1853.69     117 1855.07   133.2 1854.46   149.4 1852.63   155.9 1852.65
   165.6 1853.77   168.9 1853.54   172.1 1852.54   178.6 1849.12   182.3 1847.95
   188.3 1847.44   197.3 1848.11  202.141849.816     211 1855.17   217.5 1856.07
   230.4 1856.06   233.7 1856.72   236.9 1858.36  241.081861.516   246.6 1865.96
   249.9  1867.9   262.8 1873.67   272.6 1879.22   282.3 1882.91   298.5 1892.18
#Mann= 5 ,-1 , 0
       0     .12       0   182.3    .045       0   197.3     .12       0
  202.14    .016       0  241.08     .12       0
Bank Sta=182.3,197.3
XS Rating Curve= 0 ,0
Exp/Cntr=0.3,0.1

Type RM Length L Ch R = 1 ,21418.8 ,266,273.9,280.9
XS GIS Cut Line= 3
     2023318.846      275380.079     2023256.346      275471.225
     2023242.023       275680.86
#Sta/Elev= 30
       0 1893.46    16.2  1885.7      39 1877.36    55.3 1872.56    74.8 1868.01
      91 1862.83   100.8 1860.44   123.4 1850.52   126.7 1848.22   129.9 1845.09
   132.7 1843.43   146.1  1842.5   152.5 1842.87   162.2 1844.56   168.7 1845.02
     201 1844.21   204.3 1844.77   220.4 1850.04   226.9 1851.48   236.6 1851.72
  247.311850.668     256 1849.82   275.4 1849.56   278.6 1850.03   285.1 1852.62
  289.681853.621     298 1854.41   301.2 1855.32   307.7 1858.93   320.6 1868.25
#Mann= 5 ,-1 , 0
       0     .12       0   132.7    .045       0   152.5     .12       0
  247.31    .016       0  289.68     .12       0
Bank Sta=132.7,152.5
XS Rating Curve= 0 ,0
Exp/Cntr=0.3,0.1

Type RM Length L Ch R = 1 ,21145   ,295,296.3,297
XS GIS Cut Line= 3
     2023078.773      275318.018     2022981.171      275542.732
     2022986.389      275634.655
#Sta/Elev= 30
       0 1859.94    13.1 1856.45    32.7 1852.64    65.3 1848.71    88.2 1845.27
   117.6 1843.32   133.9 1842.83   137.2  1842.2   143.7 1838.35     147  1837.1
   153.5 1836.22   160.1 1835.52   169.9 1835.73   176.8 1836.51   186.2 1838.34
   189.5 1840.28   192.7 1842.93  197.481844.629   209.1 1845.36   225.4 1845.06
  235.421847.309   248.2 1848.86   260.9 1851.25   273.6 1855.15   283.1 1858.87
   286.3 1859.68   289.4 1860.15   295.8 1859.85   324.4 1865.21   337.1 1865.86
#Mann= 5 ,-1 , 0
       0     .12       0   153.5    .045       0   176.8     .12       0
  197.48    .016       0  235.42     .12       0
Bank Sta=153.5,176.8
XS Rating Curve= 0 ,0
Exp/Cntr=0.3,0.1

Type RM Length L Ch R = 1 ,20848.7 ,369.2,370,370.4
XS GIS Cut Line= 2
     2022822.101      275186.069     2022700.573      275470.357
#Sta/Elev= 30
       0 1856.86      26 1850.53    48.8 1845.99    58.6 1844.72    71.6 1842.23
   110.6 1838.44   113.9 1837.56   123.7 1832.42   126.9 1831.73   139.9 1831.99
   143.2 1831.69  148.65 1830.26     153 1828.83   159.5 1828.28     166 1828.85
  170.03 1830.53   175.7 1833.21     179 1833.97   201.8  1834.6   214.8 1836.08
   227.8 1839.69  233.311842.194   237.6 1843.89   244.1 1845.17   260.4 1845.99
   266.9 1845.53   270.1 1846.02  272.151846.815   283.1 1851.08   309.2 1859.74
#Mann= 5 ,-1 , 0
       0     .12       0  148.65    .045       0  170.03     .12       0
  233.31    .016       0  272.15     .12       0
Bank Sta=148.65,170.03
XS Rating Curve= 0 ,0
Exp/Cntr=0.3,0.1

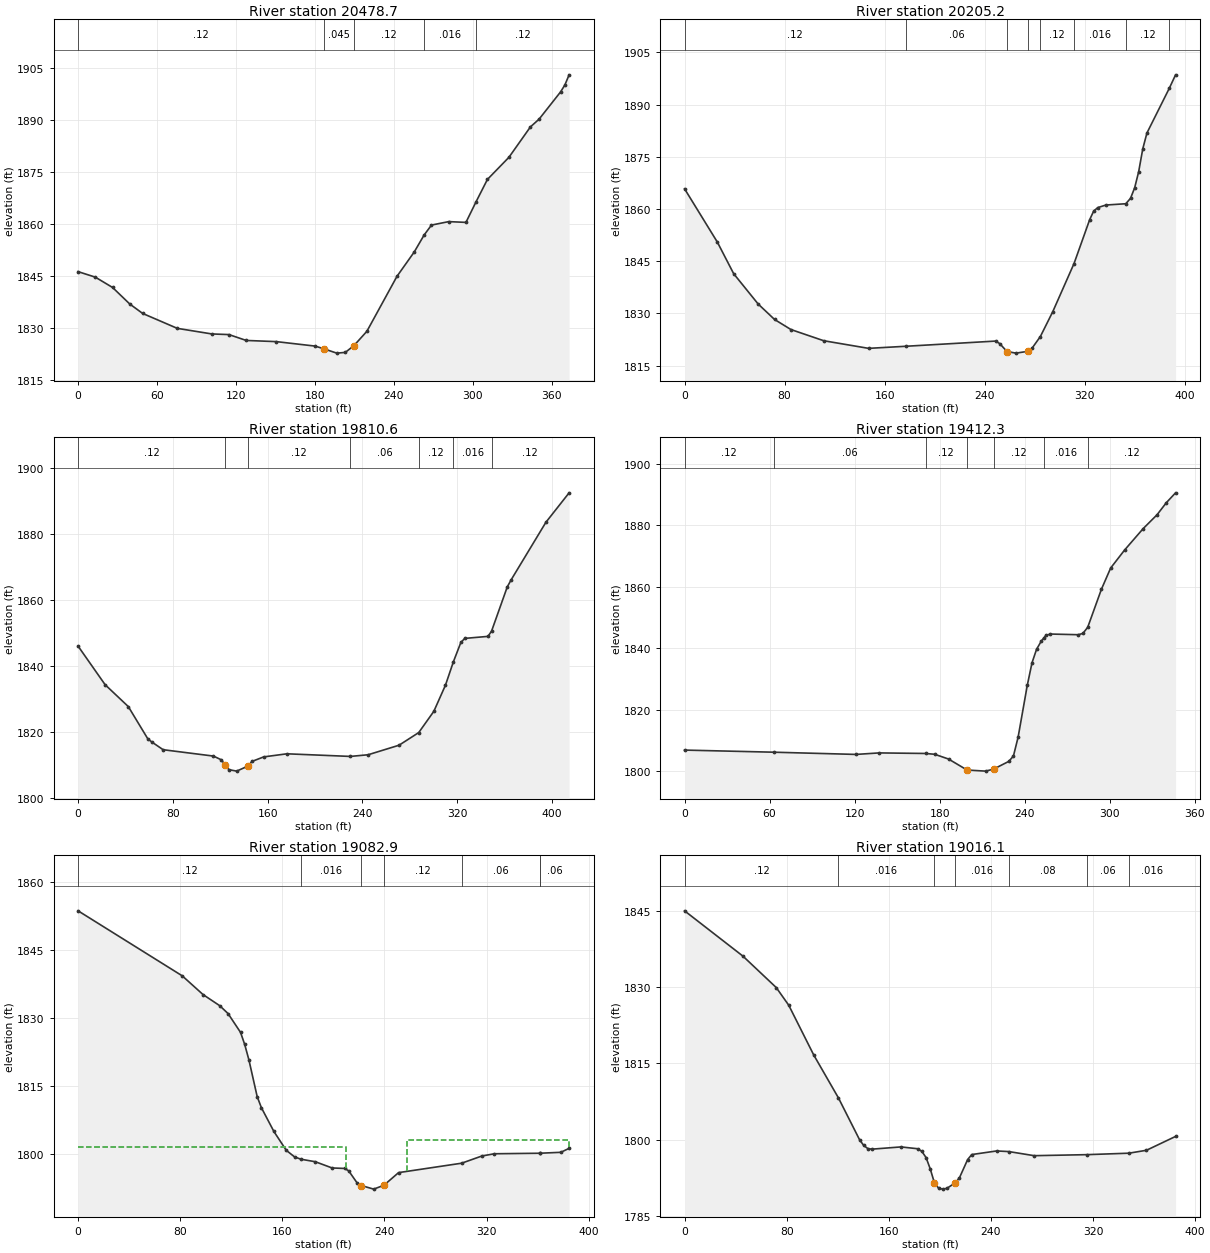
Type RM Length L Ch R = 1 ,20478.7 ,260.1,273.4,286.7
XS GIS Cut Line= 3
     2022516.546      274999.003     2022403.698      275246.399
     2022329.914      275315.843
#Sta/Elev= 30
       0 1846.34    13.1 1844.75    26.2 1841.77    39.3 1836.99    49.1 1834.27
    75.4 1829.97   101.6 1828.36   114.7 1828.17   127.8 1826.48   150.7 1826.14
   180.2 1824.85   186.7 1824.08   196.6 1822.82   203.1 1823.03   209.7    1825
   219.5 1829.12   242.4    1845   255.5 1852.02  263.021856.916   268.6 1859.78
   281.7 1860.78   294.8 1860.56  302.461866.484   311.1 1872.95   327.5 1879.36
   343.8 1888.12   350.4 1890.36   366.7 1898.21     370 1900.23   373.2 1903.15
#Mann= 5 ,-1 , 0
       0     .12       0   186.7    .045       0   209.7     .12       0
  263.02    .016       0  302.46     .12       0
Bank Sta=186.7,209.7
XS Rating Curve= 0 ,0
Exp/Cntr=0.3,0.1

Type RM Length L Ch R = 1 ,20205.2 ,394.4,394.6,394.4
XS GIS Cut Line= 2
     2022470.703      274854.691     2022136.502      275060.854
#Sta/Elev= 30
       0  1865.8    26.2 1850.51    39.3 1841.41    58.9  1832.7      72 1828.27
    85.1 1825.38   111.3 1822.17   147.2 1819.98  177.191820.584   248.7 1822.07
     252 1821.37   257.9 1819.06   265.1 1818.61   274.9 1819.14   278.1 1820.11
  284.581823.385   294.5 1830.52   311.51844.341     324 1856.93   327.2 1859.39
   330.5 1860.41     337 1861.14  352.89 1861.51   356.7 1863.08     360  1866.1
   363.2 1870.73   366.5 1877.32   369.8 1881.82   387.61894.605   392.7 1898.53
#Mann= 8 ,-1 , 0
       0     .12       0  177.19     .06       0   257.9    .045       0
   274.9     .06       0  284.58     .12       0   311.5    .016       0
  352.89     .12       0   387.6     .06       0
Bank Sta=257.9,274.9
XS Rating Curve= 0 ,0
Exp/Cntr=0.3,0.1

Type RM Length L Ch R = 1 ,19810.6 ,401.6,398.4,394.1
XS GIS Cut Line= 2
     2022326.389      274555.212     2021973.741      274773.311
#Sta/Elev= 30
       0 1845.89    22.8 1834.21    42.4 1827.57    58.8 1817.84      62  1816.9
    71.8  1814.5   114.3 1812.57   120.8 1811.46   124.1 1809.99   127.3 1808.46
   133.9 1808.01   143.3 1809.52   146.9 1810.96   156.7 1812.32   176.3 1813.26
  229.841812.466   244.9 1812.97     271 1815.86  287.641819.695   300.4 1826.14
   310.2 1834.05  316.961841.206   323.2    1847   326.5 1848.23   346.1 1848.84
  349.121850.426   362.4 1863.84   365.7    1866     395 1883.41   414.6 1892.34
#Mann= 7 ,-1 , 0
       0     .12       0   124.1    .045       0   143.3     .12       0
  229.84     .06       0  287.64     .12       0  316.96    .016       0
  349.12     .12       0
Bank Sta=124.1,143.3
XS Rating Curve= 0 ,0
Exp/Cntr=0.3,0.1

Type RM Length L Ch R = 1 ,19412.3 ,344.1,329.3,315.1
XS GIS Cut Line= 2
     2022064.887      274304.561      2021800.13      274528.085
#Sta/Elev= 30
       0 1806.88   62.911806.193     121 1805.47   137.3 1805.96  170.081805.779
   176.5 1805.52   186.3 1803.97   199.4 1800.39   212.5 1800.04   218.1  1800.7
   228.8  1803.2   232.1 1804.96   235.4 1811.11   241.9 1828.04   245.2 1835.26
   248.4 1839.63   251.7 1842.27  253.381843.232     255 1844.16   258.2  1844.6
   277.8 1844.38   281.1  1844.8   284.51846.792   294.2 1859.18   300.7 1866.06
   310.5 1871.89   323.6 1878.85   333.4 1883.35     340  1887.3   346.5  1890.5
#Mann= 7 ,-1 , 0
       0     .12       0   62.91     .06       0  170.08     .12       0
   199.4    .045       0   218.1     .12       0  253.38    .016       0
   284.5     .12       0
Bank Sta=199.4,218.1
XS Rating Curve= 0 ,0
Exp/Cntr=0.3,0.1

Type RM Length L Ch R = 1 ,19082.9 ,66.4,66.8,66.2
XS GIS Cut Line= 3
     2021939.019      274007.252     2021813.151      274061.505
     2021751.302      274301.305
#Sta/Elev= 30
       0 1853.68    81.6 1839.34    97.9 1835.21     111 1832.75   117.5 1831.02
   127.3 1826.86   130.5 1824.24   133.8 1820.85   140.3 1812.72   143.6 1810.27
   153.4 1805.02   163.1 1800.86   169.6 1799.41  174.581798.898   185.9 1798.34
     199 1796.97   208.8 1796.86     212 1796.34   218.5 1793.71   221.8  1793.1
   231.6  1792.3   239.6 1793.15   251.1 1795.94  300.521798.019   316.3  1799.6
   326.1  1800.1  361.531800.214  361.871800.219   378.2 1800.42   384.7 1801.29
#Mann= 7 ,-1 , 0
       0     .12       0  174.58    .016       0   221.8    .045       0
   239.6     .12       0  300.52     .06       0  361.53     .12       0
  361.87     .06       0
#XS Ineff= 2 , 0
          210.23 1801.59  257.39         1803.11
Permanent Ineff=
       F       F
Bank Sta=221.8,239.6
XS Rating Curve= 0 ,0
Exp/Cntr=0.3,0.1

Type RM Length L Ch R = 1 ,19016.1 ,84.7,88.9,92.3
XS GIS Cut Line= 3
      2021879.34      273993.146     2021753.472      274047.399
     2021691.623      274287.199
#Sta/Elev= 30
       0 1844.97    45.7 1836.08    71.8 1829.91    81.6 1826.44   101.2 1816.66
  120.551808.233   137.1 1800.02   140.3 1798.91   143.6 1798.27   146.8 1798.16
   169.6  1798.6   182.7 1798.24   185.9 1797.73   189.2 1796.52   192.5 1794.28
   195.7  1791.6     199  1790.5   202.2 1790.31   205.5 1790.46     212 1791.53
   215.3  1792.5   221.8 1796.12     225  1797.1   244.6 1797.81  254.081797.685
   273.9 1796.88  315.09 1797.08  348.071797.367   361.9 1797.94   384.7 1800.66
#Mann= 7 ,-1 , 0
       0     .12       0  120.55    .016       0   195.7    .045       0
     212    .016       0  254.08     .08       0  315.09     .06       0
  348.07    .016       0
Bank Sta=195.7,212
XS Rating Curve= 0 ,0
Exp/Cntr=0.3,0.1

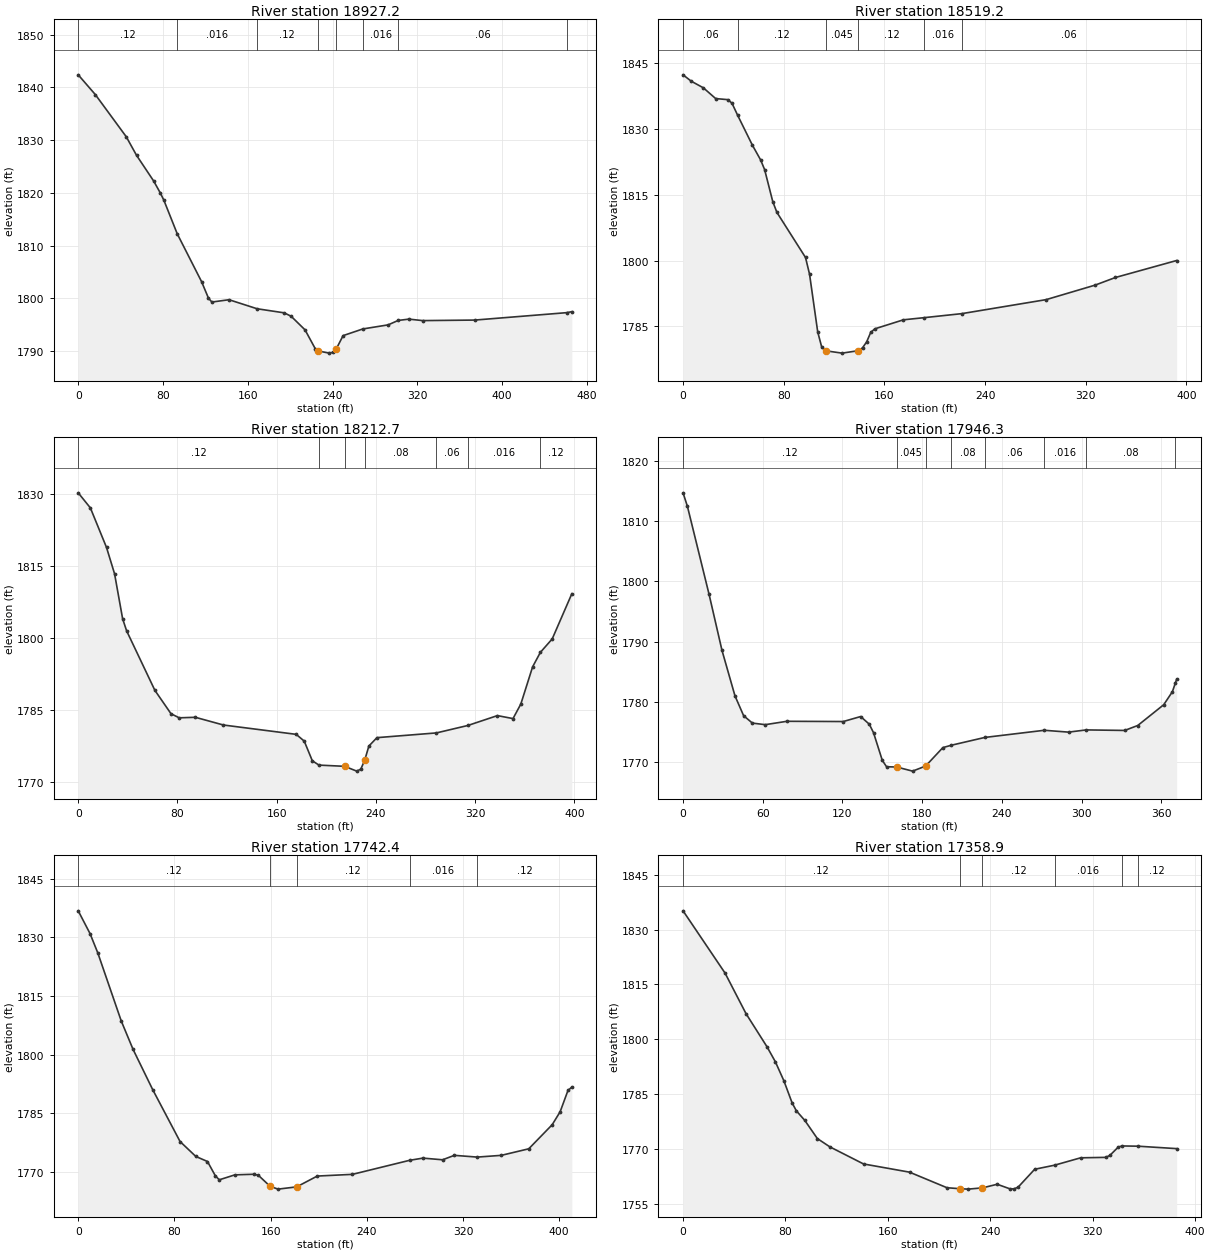
Type RM Length L Ch R = 1 ,18927.2 ,417.9,408,394.8
XS GIS Cut Line= 4
     2021861.081      273948.118     2021703.529      273984.576
     2021639.727      274127.805     2021643.633      274274.941
#Sta/Elev= 30
       0  1842.4    16.2 1838.64    45.3 1830.66      55 1827.14    71.2 1822.25
    77.6 1819.94    80.9 1818.57   93.381812.264   116.4 1803.16   122.9 1800.03
   126.1  1799.3   142.3 1799.74  168.751798.027   194.4 1797.25   200.9  1796.6
     214 1794.02   223.8 1790.39   225.9 1790.04   236.8 1789.61   240.1 1789.73
   243.4 1790.38   249.9 1792.93  268.521794.196   292.4 1794.97  301.871795.809
     312 1796.06     325 1795.78   374.1 1795.88  460.791797.285   465.7 1797.47
#Mann= 8 ,-1 , 0
       0     .12       0   93.38    .016       0  168.75     .12       0
   225.9    .045       0   243.4     .12       0  268.52    .016       0
  301.87     .06       0  460.79    .016       0
Bank Sta=225.9,243.4
XS Rating Curve= 0 ,0
Exp/Cntr=0.3,0.1

Type RM Length L Ch R = 1 ,18519.2 ,284.6,306.5,327.6
XS GIS Cut Line= 3
     2021298.828       273910.68     2021322.699      274175.437
     2021357.422      274296.965
#Sta/Elev= 30
       0 1842.25     6.5  1840.8    16.2 1839.28    25.9 1836.85    35.7  1836.6
    38.9 1835.78   43.431833.018    55.1 1826.24    61.6 1822.91    64.8  1820.7
    71.3 1813.39    74.6 1810.94    97.3  1800.7   100.5 1796.91     107 1783.76
   110.2 1780.29   113.5 1779.46   126.4 1778.94   139.4  1779.5   142.6 1780.15
   145.9  1781.5   149.1 1783.65   152.4 1784.47   175.1 1786.52  191.721787.012
  221.371787.919   288.5 1791.11   327.4 1794.41   343.6 1796.15   392.2 1800.01
#Mann= 6 ,-1 , 0
       0     .06       0   43.43     .12       0   113.5    .045       0
   139.4     .12       0  191.72    .016       0  221.37     .06       0
Bank Sta=113.5,139.4
XS Rating Curve= 0 ,0
Exp/Cntr=0.3,0.1

Type RM Length L Ch R = 1 ,18212.7 ,265.7,266.5,267.2
XS GIS Cut Line= 3
     2021176.215      273879.213     2020934.245      274091.887
     2020901.693      274160.246
#Sta/Elev= 30
       0 1830.19     9.8 1827.05    22.8 1818.82    29.3 1813.33    35.8 1803.96
      39 1801.46    61.8 1789.06    74.8 1784.19    81.4 1783.34    94.4 1783.45
   117.1 1781.84   175.7  1779.9   182.2 1778.49   188.7  1774.4  194.041773.495
   214.8 1773.24   224.5 1772.24   227.8 1772.65     231 1774.56   234.3 1777.46
   240.8 1779.21  288.761780.197  314.15 1781.75   337.9  1783.8   350.5 1783.18
   356.8 1786.21   366.3 1793.96  372.551796.969   382.1 1799.77   397.9 1809.17
#Mann= 7 ,-1 , 0
       0     .12       0  194.04     .08       0   214.8    .045       0
     231     .08       0  288.76     .06       0  314.15    .016       0
  372.55     .12       0
Bank Sta=214.8,231
XS Rating Curve= 0 ,0
Exp/Cntr=0.3,0.1

Type RM Length L Ch R = 1 ,17946.3 ,206.5,203.8,201.2
XS GIS Cut Line= 2
     2020987.413      273707.772      2020699.87      273943.232
#Sta/Elev= 30
       0 1814.73     3.3 1812.47    19.6 1797.85    29.3 1788.56    39.1 1780.99
    45.6  1777.7    52.2 1776.47    61.9 1776.21    78.2 1776.77   120.6 1776.73
   133.7 1777.56   140.2 1776.29   143.4 1774.87     150 1770.28   153.2 1769.22
   160.9 1769.17   172.8 1768.49   182.6 1769.33   195.6  1772.4  202.041772.795
  227.181774.087  271.961775.276   290.2 1774.97  303.541775.338   332.5 1775.25
   342.3 1776.07   361.9 1779.53   368.4 1781.69  370.671783.151   371.6 1783.75
#Mann= 8 ,-1 , 0
       0     .12       0   160.9    .045       0   182.6     .12       0
  202.04     .08       0  227.18     .06       0  271.96    .016       0
  303.54     .08       0  370.67     .06       0
Bank Sta=160.9,182.6
XS Rating Curve= 0 ,0
Exp/Cntr=0.3,0.1

Type RM Length L Ch R = 1 ,17742.4 ,378.8,383.5,387.5
XS GIS Cut Line= 2
     2020841.797       273539.37     2020556.423      273834.508
#Sta/Elev= 30
       0 1836.83     9.8 1831.01    16.3 1826.03    35.8 1808.58    45.6 1801.32
    61.9 1791.02    84.7 1777.69    97.8 1773.87   107.5 1772.57     114 1768.93
   117.3 1767.88   130.3 1769.15   146.6 1769.31   149.9 1769.01   159.7 1766.18
   166.2 1765.49   181.7 1766.07   198.8 1768.84   228.1 1769.28  275.691772.883
   286.7 1773.44     303 1773.01   312.8 1774.15  331.871773.701   351.9 1774.15
   374.7 1775.83   394.2 1782.01   400.8 1785.33   407.3 1790.79   410.5 1791.64
#Mann= 5 ,-1 , 0
       0     .12       0   159.7    .045       0   181.7     .12       0
  275.69    .016       0  331.87     .12       0
Bank Sta=159.7,181.7
XS Rating Curve= 0 ,0
Exp/Cntr=0.3,0.1

Type RM Length L Ch R = 1 ,17358.9 ,307.8,286,263.8
XS GIS Cut Line= 3
     2020589.193      273295.446     2020480.686      273409.378
     2020303.819      273553.693
#Sta/Elev= 30
       0 1835.13    32.8 1818.12    49.2 1807.02    65.6 1797.96    72.1 1793.88
    78.7 1788.73    85.2 1782.63    88.5 1780.47    95.1 1777.85   104.9 1772.89
   114.7 1770.61     141 1765.94   176.9  1763.7   206.2 1759.44     216 1759.18
   222.6 1759.06   233.9  1759.4   245.4 1760.39   255.2 1759.16   258.4 1759.12
   261.7 1759.58   274.7 1764.49  290.221765.602   310.6 1767.62   330.2 1767.74
   333.4 1768.27     340 1770.56  342.931770.862  355.321770.798   385.6 1770.13
#Mann= 6 ,-1 , 0
       0     .12       0     216    .045       0   233.9     .12       0
  290.22    .016       0  342.93     .08       0  355.32     .12       0
Bank Sta=216,233.9
XS Rating Curve= 0 ,0
Exp/Cntr=0.3,0.1

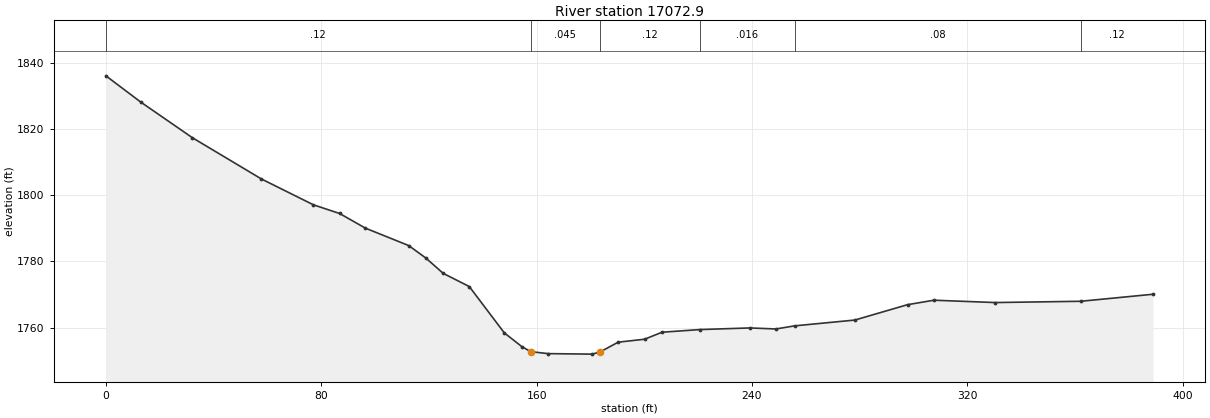
Type RM Length L Ch R = 1 ,17072.9 ,275.8,275.2,274
XS GIS Cut Line= 3
     2020287.543      273145.706     2020207.248      273254.213
     2020201.823       273508.12
#Sta/Elev= 30
       0 1836.08    12.9 1828.18    32.1  1817.4    57.8 1804.91    77.1 1797.11
    86.8  1794.5    96.4 1790.07   112.5  1784.8   118.9 1781.01   125.3 1776.41
     135 1772.42     148 1758.43   154.5 1754.29   157.8 1752.76   164.3 1752.16
   180.6 1752.01   183.5 1752.63   190.3 1755.62   200.1 1756.51   206.6 1758.63
  220.761759.432   239.2 1759.92   248.9 1759.61  255.841760.548   278.2  1762.3
   297.8 1766.95   307.6  1768.3   330.3 1767.59  362.131767.974     389  1770.1
#Mann= 6 ,-1 , 0
       0     .12       0   157.8    .045       0   183.5     .12       0
  220.76    .016       0  255.84     .08       0  362.13     .12       0
Bank Sta=157.8,183.5
XS Rating Curve= 0 ,0
Exp/Cntr=0.3,0.1