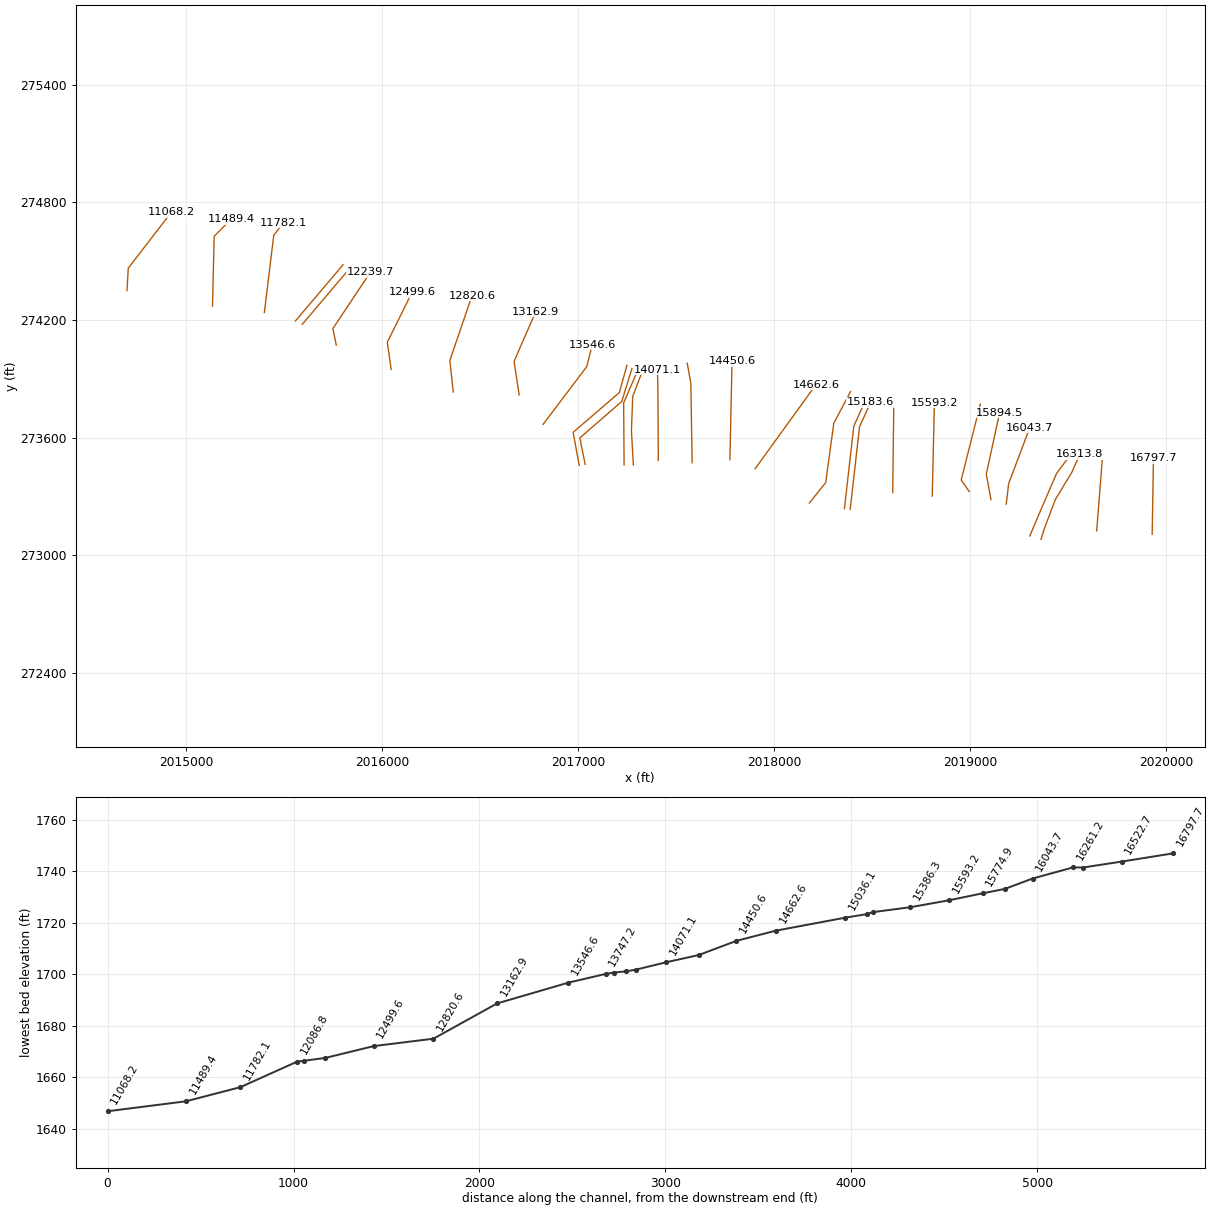
HEC-RAS study LAURELCK.prj: LAURELCK

--- LAURELCK.g01 (geometry) --- (continued)

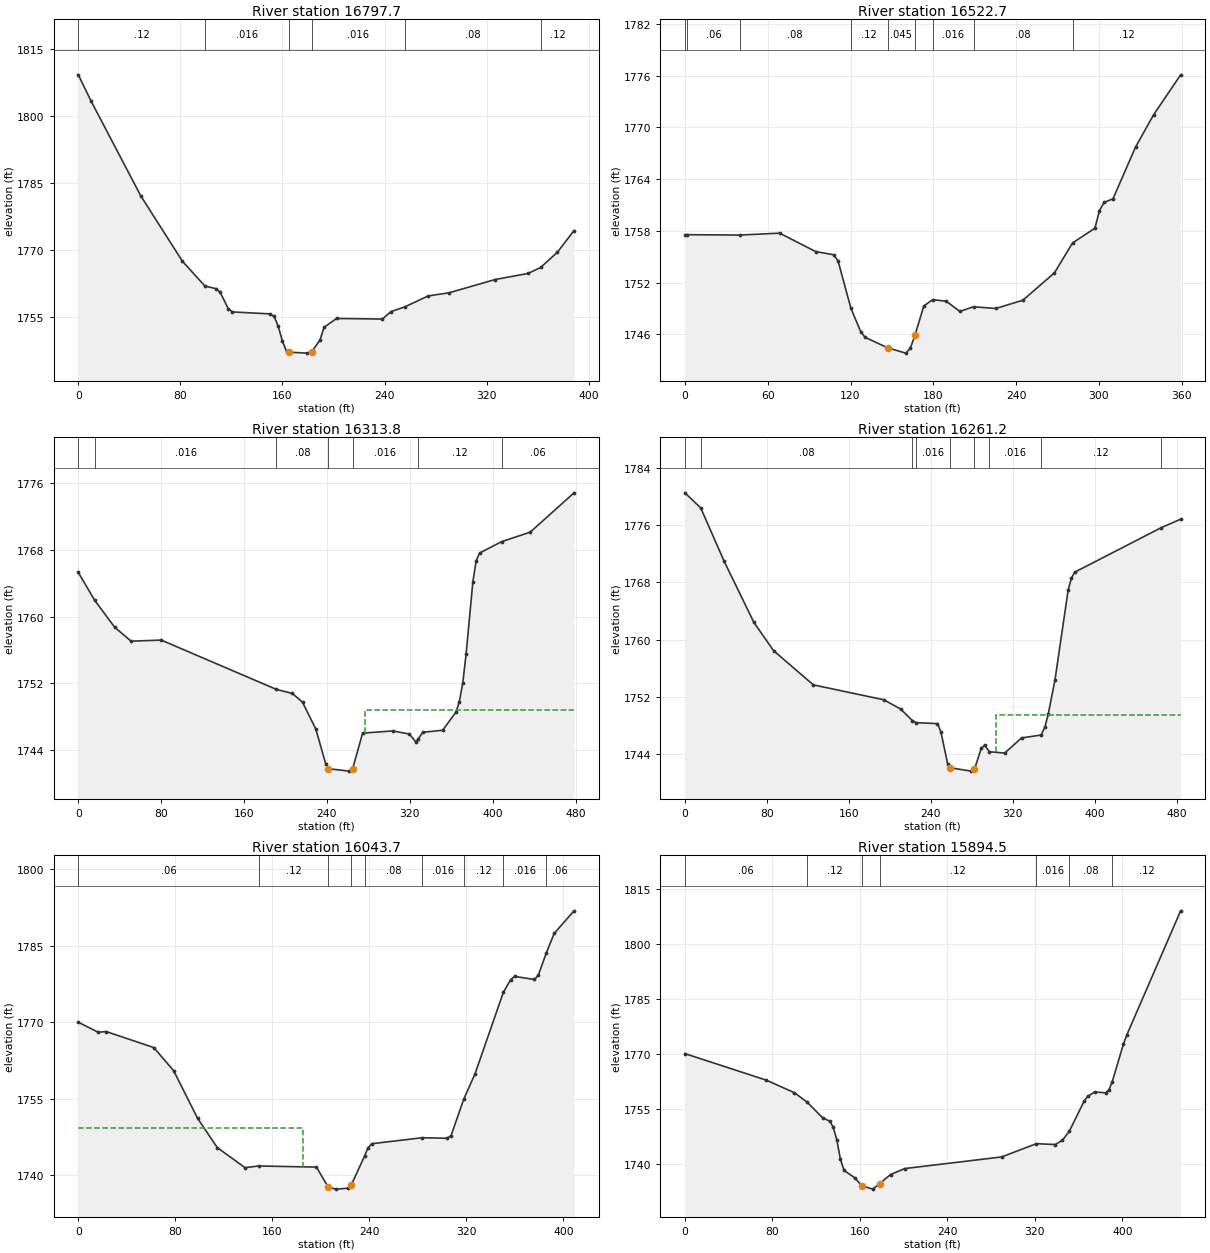
Type RM Length L Ch R = 1 ,16797.7 ,276.2,275,273.5
XS GIS Cut Line= 2
      2019929.47      273107.729     2019935.981      273496.184
#Sta/Elev= 30
       0  1809.2     9.8 1803.44      49 1782.12    81.6 1767.52   99.231762.006
   107.7 1761.42     111 1760.69   117.5 1756.93   120.8 1756.21   150.2 1755.77
   153.4 1755.24   156.7 1752.98     160 1749.62   163.2 1747.39     165 1747.21
   179.6    1747   182.8 1747.28   189.4 1749.93   192.6 1752.78   202.4 1754.75
   238.3 1754.61   244.9 1756.26  255.811757.338   274.2 1759.78   290.6 1760.49
   326.5 1763.44   352.6 1764.82  362.391766.168   375.4 1769.53   388.5  1774.4
#Mann= 6 ,-1 , 0
       0     .12       0   99.23    .016       0     165    .045       0
   182.8    .016       0  255.81     .08       0  362.39     .12       0
Bank Sta=165,182.8
XS Rating Curve= 0 ,0
Exp/Cntr=0.3,0.1

Type RM Length L Ch R = 1 ,16522.7 ,219.3,209,198.3
XS GIS Cut Line= 2
     2019646.267       273125.09     2019674.479      273483.163
#Sta/Elev= 30
       0 1757.54    1.761757.561   39.661757.519    68.6 1757.74    94.7 1755.61
   107.8 1755.23     111 1754.51  120.281749.029   127.4  1746.3   130.6 1745.65
   146.9 1744.44     160 1743.82   163.3 1744.36   166.7 1745.89   173.1 1749.29
  179.531750.026   189.4 1749.84   199.2 1748.66  209.16  1749.2   225.3    1749
   244.9 1749.96   267.8 1753.14  280.891756.607   297.1 1758.31   300.4 1760.36
   303.7  1761.3   310.2 1761.73   326.5 1767.72   339.6 1771.47   359.2 1776.11
#Mann= 9 ,-1 , 0
       0     .12       0    1.76     .06       0   39.66     .08       0
  120.28     .12       0   146.9    .045       0   166.7     .08       0
  179.53    .016       0  209.16     .08       0  280.89     .12       0
Bank Sta=146.9,166.7
XS Rating Curve= 0 ,0
Exp/Cntr=0.3,0.1

Type RM Length L Ch R = 1 ,16313.8 ,49.2,52.5,55.9
XS GIS Cut Line= 5
     2019362.383      273082.233      2019379.31       273136.92
     2019435.764       273285.68     2019519.314      273423.484
     2019560.547      273515.715
#Sta/Elev= 30
       0 1765.27   15.771761.941      35 1758.73    50.9 1757.05      80 1757.18
  191.211751.282   206.6  1750.8   216.4 1749.75   229.2 1746.55   238.9 1742.34
  241.36  1741.8   261.5 1741.51   264.7 1741.76   274.4 1746.05   303.4 1746.32
   319.5 1745.95   325.9 1744.98  328.171745.386   332.4 1746.15   351.7  1746.4
   364.6 1748.59   367.8 1749.82   371.1 1752.07   374.3 1755.52   380.8 1764.12
     384 1766.66   387.3 1767.59  408.481768.946   436.2 1770.09   478.5 1774.79
#Mann= 7 ,-1 , 0
       0     .12       0   15.77    .016       0  191.21     .08       0
  241.36    .045       0   264.7    .016       0  328.17     .12       0
  408.48     .06       0
#XS Ineff= 2 , 0
                          276.99         1748.83
Permanent Ineff=
       F       F
Bank Sta=241.36,264.7
XS Rating Curve= 0 ,0
Exp/Cntr=0.3,0.1

Type RM Length L Ch R = 1 ,16261.2 ,216.8,217.6,218.3
XS GIS Cut Line= 4
     2019305.091       273099.16     2019348.696      273202.489
     2019442.274      273419.144     2019523.654      273527.651
#Sta/Elev= 30
       0 1780.56   15.451778.443    38.4 1770.94    67.3 1762.41    86.5 1758.45
   125.3 1753.65   194.1 1751.56   210.5 1750.27  221.931748.652  225.991748.344
   246.5 1748.22   249.8 1747.08   256.4 1742.61   258.4 1742.05   279.3 1741.56
   282.6  1741.8   289.2 1744.75   292.4 1745.19  297.261744.276   312.1 1744.09
   328.5 1746.21  347.731746.623   351.4 1747.77   354.6 1749.57   361.1 1754.27
     374  1766.9   377.2  1768.6   380.4 1769.44  464.331775.638   483.8 1776.87
#Mann= 9 ,-1 , 0
       0     .12       0   15.45     .08       0  221.93     .06       0
  225.99    .016       0   258.4    .045       0   282.6     .08       0
  297.26    .016       0  347.73     .12       0  464.33     .06       0
#XS Ineff= 2 , 0
                          303.98         1749.36
Permanent Ineff=
       F       F
Bank Sta=258.4,282.6
XS Rating Curve= 0 ,0
Exp/Cntr=0.3,0.1

Type RM Length L Ch R = 1 ,16043.7 ,145.7,149.2,151.9
XS GIS Cut Line= 3
     2019185.113      273261.809     2019197.048      273365.976
      2019304.47      273650.264
#Sta/Elev= 30
       0    1770    16.4 1768.03    22.9 1768.18    62.2 1765.03    78.6 1760.49
    98.3 1751.16   114.6 1745.39   137.5 1741.45  148.751741.786   196.4 1741.56
   206.2 1737.58   212.7 1737.24   222.5 1737.42     225 1738.02  236.131743.768
   238.8 1745.32   242.1 1746.16  283.611747.329   304.2 1747.23   307.4 1747.76
  317.851754.901   327.1 1759.85  350.551775.905   356.5 1778.35   359.7    1779
   376.1 1778.39   379.3 1779.23     3861783.646   392.4 1787.43   408.8 1791.87
#Mann= 9 ,-1 , 0
       0     .06       0  148.75     .12       0   206.2    .045       0
     225     .12       0  236.13     .08       0  283.61    .016       0
  317.85     .12       0  350.55    .016       0     386     .06       0
#XS Ineff= 2 , 0
          185.37 1749.17
Permanent Ineff=
       F       F
Bank Sta=206.2,225
XS Rating Curve= 0 ,0
Exp/Cntr=0.3,0.1

Type RM Length L Ch R = 1 ,15894.5 ,119.5,119.6,118.6
XS GIS Cut Line= 3
     2019106.988      273284.595     2019083.116      273414.804
     2019151.476      273728.389
#Sta/Elev= 30
       0 1770.18    74.3 1762.95   100.1 1759.52   111.71756.954   125.9 1752.68
   132.4 1751.73   135.6 1750.15   138.9 1746.66   142.2 1741.38   145.5 1738.31
   155.3 1736.29   161.8 1734.12   171.7  1733.2   178.2 1734.71     188 1737.18
   201.2 1738.82   289.6 1741.98  321.351745.599   338.7 1745.37   345.2 1746.54
  351.581749.028   364.9 1757.12   368.2 1758.49   374.7 1759.72   384.6 1759.48
   387.8 1760.34  390.77  1762.5   400.9 1772.69   404.2 1775.36   453.3 1809.14
#Mann= 7 ,-1 , 0
       0     .06       0   111.7     .12       0   161.8    .045       0
   178.2     .12       0  321.35    .016       0  351.58     .08       0
  390.77     .12       0
Bank Sta=161.8,178.2
XS Rating Curve= 0 ,0
Exp/Cntr=0.3,0.1

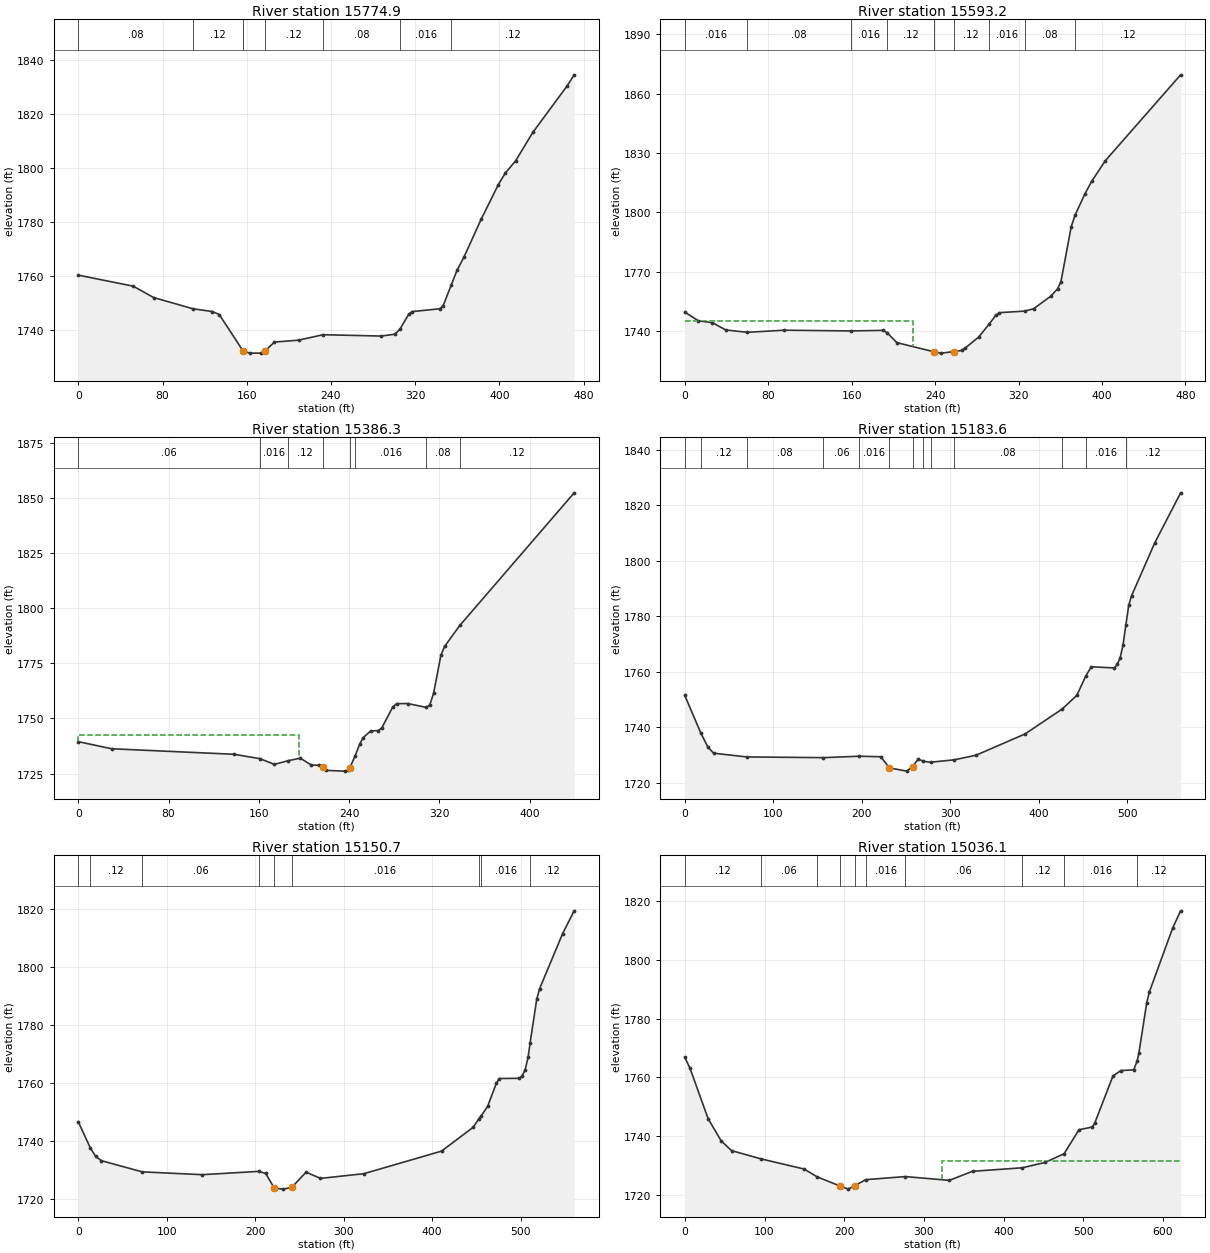
Type RM Length L Ch R = 1 ,15774.9 ,176.6,181.7,186.7
XS GIS Cut Line= 3
     2018996.311      273325.828     2018955.078      273384.422
     2019052.734      273771.791
#Sta/Elev= 30
       0 1760.34    52.1 1756.27    71.6 1752.04  108.871747.904   127.3 1746.87
   133.9 1745.77   156.8 1732.11   163.3 1731.48   173.2 1731.49   177.1 1732.16
   186.3 1735.57   209.2 1736.28  232.47 1738.29   287.8  1737.8   300.9 1738.49
  305.641740.398     314 1745.95   317.2 1746.86   343.4  1747.9   346.7  1749.1
  354.311756.667   359.8 1762.12   366.4 1767.03   382.7 1780.99   399.1 1793.88
   405.6 1798.08   415.5 1802.66   431.8 1813.16   464.6 1830.48   471.1 1834.48
#Mann= 7 ,-1 , 0
       0     .08       0  108.87     .12       0   156.8    .045       0
   177.1     .12       0  232.47     .08       0  305.64    .016       0
  354.31     .12       0
Bank Sta=156.8,177.1
XS Rating Curve= 0 ,0
Exp/Cntr=0.3,0.1

Type RM Length L Ch R = 1 ,15593.2 ,207.5,206.9,207.6
XS GIS Cut Line= 2
     2018807.509      273303.041     2018818.359      273778.302
#Sta/Elev= 30
       0 1749.55    13.1 1745.07    26.2 1744.23    39.3 1740.48    60.11739.293
    95.1 1740.36  159.481739.992   190.2 1740.27  193.921739.121   203.3 1734.07
   239.3 1729.39   245.9 1728.76   257.7 1729.53   265.6 1730.14   268.8  1731.3
     282 1737.02  291.66 1743.38   298.3 1747.95   301.6 1749.23  326.011750.038
   334.4 1751.21   350.8 1757.51   357.4 1761.28   360.6 1764.83   370.5 1792.69
  374.141798.502   383.6 1809.31   390.1 1815.65   403.3 1826.17   475.4 1869.55
#Mann= 9 ,-1 , 0
       0    .016       0    60.1     .08       0  159.48    .016       0
  193.92     .12       0   239.3    .045       0   257.7     .12       0
  291.66    .016       0  326.01     .08       0  374.14     .12       0
#XS Ineff= 2 , 0
          218.75 1744.87
Permanent Ineff=
       F       F
Bank Sta=239.3,257.7
XS Rating Curve= 0 ,0
Exp/Cntr=0.3,0.1

Type RM Length L Ch R = 1 ,15386.3 ,204.7,202.6,198.4
XS GIS Cut Line= 2
     2018605.686      273320.403     2018611.111      273759.856
#Sta/Elev= 30
       0 1739.43    29.5 1736.22   137.8 1733.72  160.891731.738   173.8 1729.14
  185.841730.794   196.8 1731.96   206.6 1728.79   213.2 1728.75   216.5 1727.73
   219.7 1726.42   236.1 1726.08   239.4 1726.43  240.62 1727.57   245.31732.917
   249.3 1738.23   252.5 1741.29   259.1 1744.26   265.7 1744.47   268.9 1745.56
   278.8 1755.26   282.1 1756.64   291.9 1756.71  308.591754.959   311.6 1756.19
   314.9 1761.36   321.4 1778.63   324.7 1782.63  338.131792.099   439.5  1852.2
#Mann= 8 ,-1 , 0
       0     .06       0  160.89    .016       0  185.84     .12       0
   216.5    .045       0  240.62     .12       0   245.3    .016       0
  308.59     .08       0  338.13     .12       0
#XS Ineff= 2 , 0
          196.02 1742.65
Permanent Ineff=
       F       F
Bank Sta=216.5,240.62
XS Rating Curve= 0 ,0
Exp/Cntr=0.3,0.1

Type RM Length L Ch R = 1 ,15183.6 ,33.4,33,33.4
XS GIS Cut Line= 3
     2018388.672      273234.682     2018436.415      273655.689
     2018492.838      273780.472
#Sta/Elev= 30
       0 1751.47      181737.984    26.1 1732.83    32.6 1730.64   69.81 1729.28
  156.791729.024  197.251729.532   221.6 1729.35   231.4 1725.32     251 1724.16
   257.5 1725.82     264  1728.5  269.861727.706   277.91727.375  304.591728.237
   329.2 1729.89   384.6 1737.55  426.791746.588   443.3 1751.53  453.321758.459
   459.6 1761.81   485.7 1761.39   488.9 1762.63   492.2 1765.01   495.4 1769.52
  498.641776.786     502 1784.11   505.2 1787.49   531.3 1806.48   560.6 1824.56
#Mann= 13 ,-1 , 0
       0    .016       0      18     .12       0   69.81     .08       0
  156.79     .06       0  197.25    .016       0   231.4    .045       0
   257.5    .016       0  269.86     .12       0   277.9    .016       0
  304.59     .08       0  426.79     .12       0  453.32    .016       0
  498.64     .12       0
Bank Sta=231.4,257.5
XS Rating Curve= 0 ,0
Exp/Cntr=0.3,0.1

Type RM Length L Ch R = 1 ,15150.7 ,114.6,114.6,114.9
XS GIS Cut Line= 3
     2018359.375      273237.937     2018407.118      273658.944
     2018463.542      273783.727
#Sta/Elev= 30
       0 1746.56   13.441737.664    19.6 1734.63    26.1 1733.17   72.121729.322
   140.2 1728.35  203.991729.489   211.8 1728.76   221.6 1723.72   231.4 1723.37
   241.2 1723.95   257.5 1729.22   273.8 1727.07   322.7 1728.68   410.7 1736.47
   446.5  1744.7  452.73 1747.58  455.641748.686   462.8 1751.91   472.6 1759.85
   475.9 1761.48   498.7 1761.55     502 1762.46   505.2 1764.57   508.5 1768.73
  510.751773.694   518.3 1788.83   521.5 1792.42   547.6 1811.44   560.6 1819.26
#Mann= 9 ,-1 , 0
       0    .016       0   13.44     .12       0   72.12     .06       0
  203.99    .016       0   221.6    .045       0   241.2    .016       0
  452.73     .12       0  455.64    .016       0  510.75     .12       0
Bank Sta=221.6,241.2
XS Rating Curve= 0 ,0
Exp/Cntr=0.3,0.1

Type RM Length L Ch R = 1 ,15036.1 ,384.1,373.4,362.3
XS GIS Cut Line= 4
     2018180.338      273267.234     2018263.889      273371.401
     2018305.121      273674.135     2018390.842      273835.811
#Sta/Elev= 30
       0 1766.84     6.5 1763.18    29.3 1745.95    45.6 1738.46    58.6 1735.13
   95.461732.317   149.8 1728.85  166.051726.191   195.3 1723.02     205 1722.02
   213.4 1723.21     2271725.242  276.641726.289   331.8    1725   361.1 1728.09
  423.281729.279   452.1  1731.1  475.941734.088   494.6 1742.22     511 1743.14
   514.2 1744.38   537.1 1760.45   546.9 1762.35   563.2 1762.61  567.651765.665
   569.8 1768.44   579.6 1785.45   582.8 1789.05   612.2 1810.91   622.1  1816.7
#Mann= 10 ,-1 , 0
       0     .12       0   95.46     .06       0  166.05     .12       0
   195.3    .045       0   213.4     .12       0     227    .016       0
  276.64     .06       0  423.28     .12       0  475.94    .016       0
  567.65     .12       0
#XS Ineff= 2 , 0
                          322.16         1731.59
Permanent Ineff=
       F       F
Bank Sta=195.3,213.4
XS Rating Curve= 0 ,0
Exp/Cntr=0.3,0.1

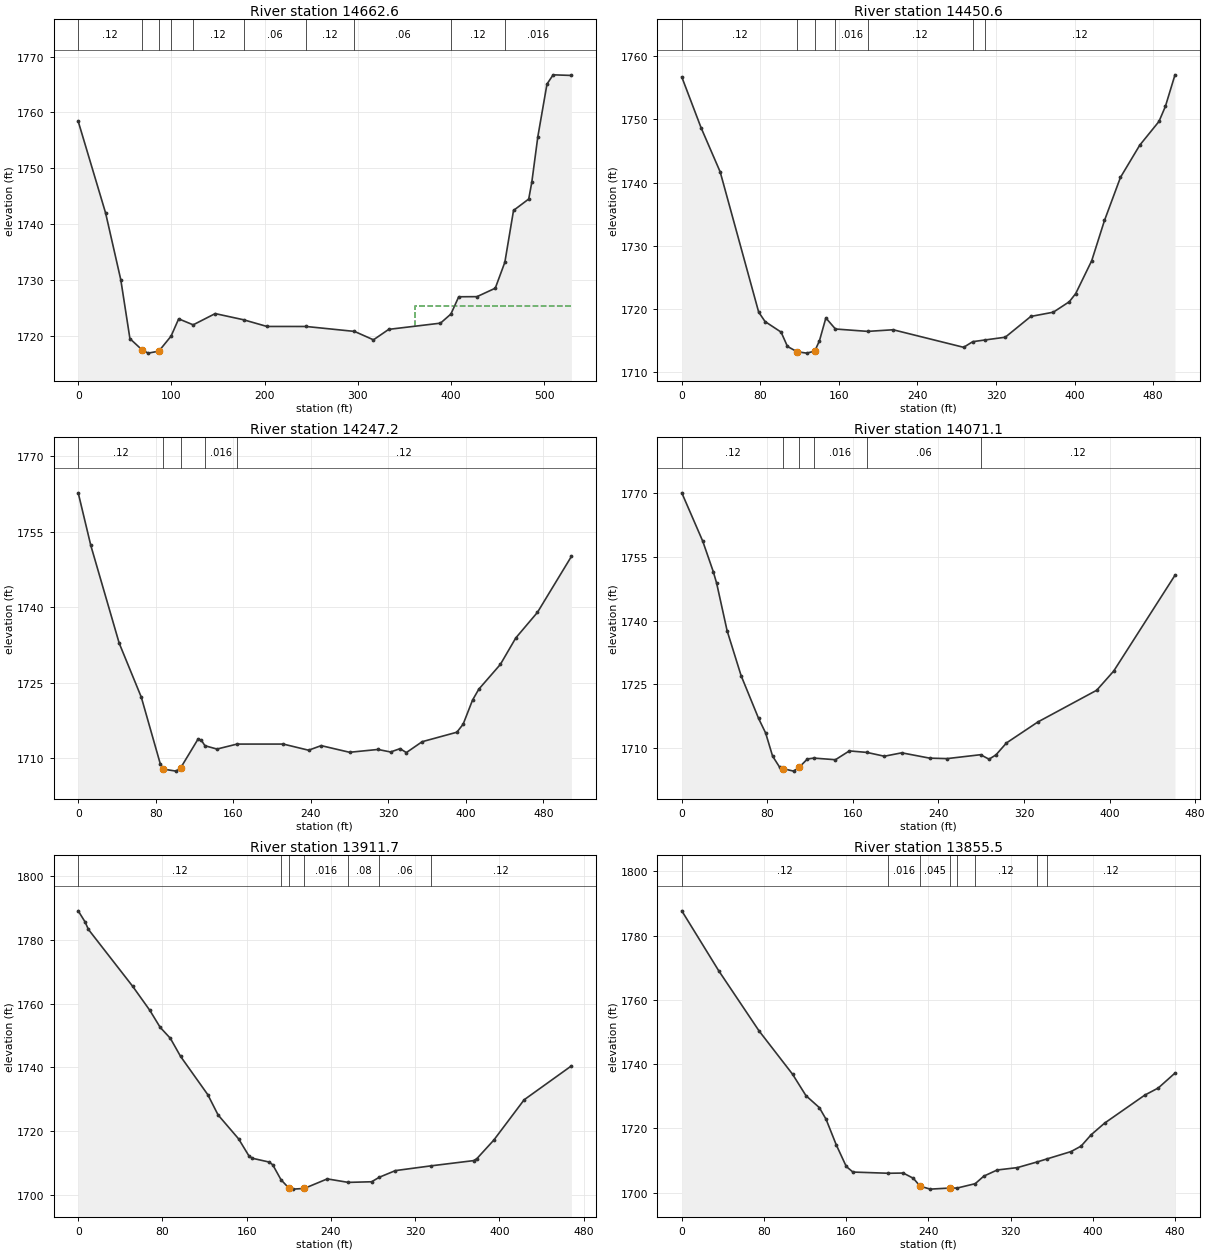
Type RM Length L Ch R = 1 ,14662.6 ,198,212.1,225.2
XS GIS Cut Line= 2
     2017903.646       273441.93     2018213.976      273870.533
#Sta/Elev= 30
       0 1758.42    29.4 1742.02    45.7 1730.08    55.5 1719.55    68.6 1717.53
    75.1 1716.96    86.5 1717.31   99.631719.993   107.8 1723.09  123.39 1722.02
     147 1724.03  177.411722.927   202.5 1721.73  244.411721.727  296.451720.844
   316.8 1719.34   333.2 1721.21   388.7 1722.32   399.91723.948   408.3 1727.04
   427.9 1727.06   447.5 1728.57  457.781733.208   467.1 1742.48   483.4 1744.52
   486.7 1747.52   493.2 1755.69     503 1765.08   509.6 1766.73   529.2 1766.62
#Mann= 10 ,-1 , 0
       0     .12       0    68.6    .045       0    86.5     .12       0
   99.63    .016       0  123.39     .12       0  177.41     .06       0
  244.41     .12       0  296.45     .06       0   399.9     .12       0
  457.78    .016       0
#XS Ineff= 2 , 0
                          361.36         1725.44
Permanent Ineff=
       F       F
Bank Sta=68.6,86.5
XS Rating Curve= 0 ,0
Exp/Cntr=0.3,0.1

Type RM Length L Ch R = 1 ,14450.6 ,202.7,203.4,204.1
XS GIS Cut Line= 2
     2017775.143      273488.483     2017786.024      273990.541
#Sta/Elev= 30
       0 1756.72    19.6  1748.7    39.1 1741.69    78.3 1719.49    84.8    1718
   101.1 1716.33   107.6 1714.06   117.4 1713.22   127.2    1713   135.4 1713.32
   140.2 1714.97   146.7 1718.57  156.451716.819  189.361716.442   215.2  1716.7
     287 1713.92  296.291714.815   309.21715.093   329.4 1715.52   355.4 1718.81
   378.3 1719.48   394.6 1721.14   401.1 1722.43   417.4 1727.63   430.4    1734
   446.7 1740.83   466.3 1745.92   485.9 1749.68   492.4 1752.05   502.2 1757.06
#Mann= 7 ,-1 , 0
       0     .12       0   117.4    .045       0   135.4     .12       0
  156.45    .016       0  189.36     .12       0  296.29     .06       0
   309.2     .12       0
Bank Sta=117.4,135.4
XS Rating Curve= 0 ,0
Exp/Cntr=0.3,0.1

Type RM Length L Ch R = 1 ,14247.2 ,175.9,176.1,176.2
XS GIS Cut Line= 3
     2017582.435      273472.858     2017575.925      273876.503
     2017557.509      273980.125
#Sta/Elev= 30
       0 1762.71      13 1752.27    42.3 1732.87    65.1 1722.16    84.6 1708.99
    87.9 1707.88   100.9 1707.48   105.6 1708.09   123.7 1713.85     127 1713.62
   130.81712.518   143.2 1711.86  163.861712.847   211.6 1712.85   237.7 1711.63
   250.7 1712.54     280 1711.22   309.3 1711.78   322.3 1711.28   332.1 1711.94
   338.6 1711.16   354.9 1713.32   390.7  1715.2   397.2  1716.8   406.9 1721.58
   413.3 1723.73   435.6 1728.66   451.5 1733.91   473.9    1739   508.9 1750.09
#Mann= 5 ,-1 , 0
       0     .12       0    87.9    .045       0   105.6     .12       0
   130.8    .016       0  163.86     .12       0
Bank Sta=87.9,105.6
XS Rating Curve= 0 ,0
Exp/Cntr=0.3,0.1

Type RM Length L Ch R = 1 ,14071.1 ,155.9,159.4,162.2
XS GIS Cut Line= 3
     2017409.939      273485.333     2017407.769      273851.002
     2017405.599      273946.488
#Sta/Elev= 30
       0 1770.02    19.6 1758.66    29.4 1751.54    32.6 1748.78    42.4 1737.61
    55.5 1727.06    71.8 1717.04    78.4 1713.61    84.9 1708.18    91.4 1705.61
    94.7 1705.23   104.5 1704.65   109.7 1705.54   117.5 1707.51  123.52 1707.71
   143.7 1707.33   156.7  1709.4  173.151709.045   189.4 1708.15   205.7 1708.95
   231.8  1707.7   248.1 1707.59   279.41708.508   287.3 1707.45   293.8 1708.47
   303.6 1711.27     333  1716.2     388 1723.65   403.9 1728.16   461.2 1750.66
#Mann= 6 ,-1 , 0
       0     .12       0    94.7    .045       0   109.7     .12       0
  123.52    .016       0  173.15     .06       0   279.4     .12       0
Bank Sta=94.7,109.7
XS Rating Curve= 0 ,0
Exp/Cntr=0.3,0.1

Type RM Length L Ch R = 1 ,13911.7 ,56.6,56.2,56.8
XS GIS Cut Line= 4
     2017282.552      273461.462     2017272.786      273636.158
     2017279.297      273810.854     2017321.614      273921.531
#Sta/Elev= 30
       0  1789.1     6.5 1785.63     9.7 1783.27    51.8  1765.4      68  1757.9
    77.8 1752.58    87.5 1749.13    97.2 1743.46   123.1 1731.43   132.8 1725.11
   152.3  1717.6     162 1712.32   165.2 1711.53   181.4 1710.32   184.7 1709.47
  192.621704.755   199.7 1702.29   204.1 1701.84   214.7 1702.06   236.5 1705.05
  256.421703.955   278.6 1704.15  285.981705.575   301.2 1707.65  334.761709.129
   375.4 1710.78   378.6 1711.42   394.6 1717.21   423.4 1729.85   468.3 1740.48
#Mann= 7 ,-1 , 0
       0     .12       0  192.62    .016       0   199.7    .045       0
   214.7    .016       0  256.42     .08       0  285.98     .06       0
  334.76     .12       0
Bank Sta=199.7,214.7
XS Rating Curve= 0 ,0
Exp/Cntr=0.3,0.1

Type RM Length L Ch R = 1 ,13855.5 ,88.2,65.7,42.1
XS GIS Cut Line= 3
     2017235.243      273461.462     2017233.073      273778.302
     2017298.177      273928.041
#Sta/Elev= 30
       0 1787.68    35.9 1769.07    75.1 1750.39   107.8 1736.88   120.9 1730.19
   133.9 1726.48   140.5 1722.83   150.3 1714.95   160.1 1708.18   166.6 1706.44
  201.121706.064   215.6 1706.13   225.4  1704.5   231.9 1702.08   241.7 1701.13
   261.3 1701.47     2681701.464  285.641702.827     294 1705.17     307 1707.08
   326.6 1707.82  346.181709.609  355.391710.516   378.9 1712.81   388.7 1714.51
   398.5 1718.04   411.6 1721.66   450.7 1730.37   463.8 1732.58   480.1 1737.22
#Mann= 8 ,-1 , 0
       0     .12       0  201.12    .016       0   231.9    .045       0
   261.3    .016       0     268     .08       0  285.64     .12       0
  346.18     .06       0  355.39     .12       0
Bank Sta=231.9,261.3
XS Rating Curve= 0 ,0
Exp/Cntr=0.3,0.1

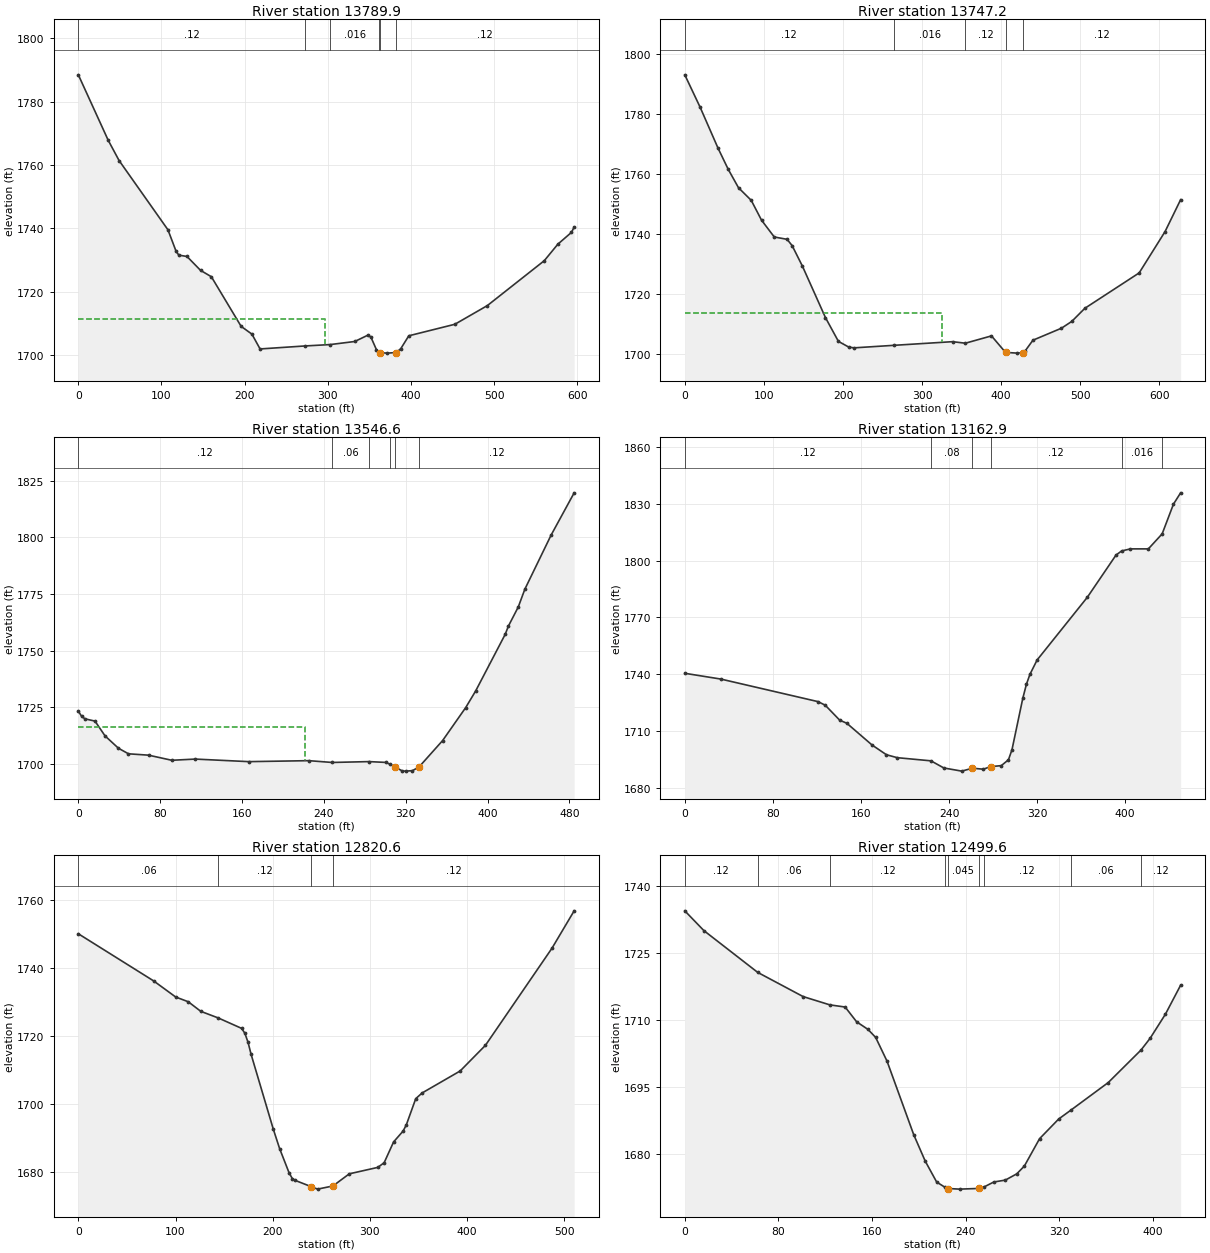
Type RM Length L Ch R = 1 ,13789.9 ,42.8,42.7,42.6
XS GIS Cut Line= 4
     2017036.675      273464.717     2017009.548      273599.265
     2017223.307      273784.812      2017275.39      273952.998
#Sta/Elev= 30
       0 1788.46      36 1767.78      49 1761.43   107.8 1739.57   117.6 1732.78
   120.9 1731.58   130.7 1731.16     147 1726.78     160 1724.77   195.8 1709.12
   208.8 1706.66   218.6 1701.99  272.651702.932  302.981703.371   332.5 1704.34
   348.7 1706.39     352 1705.67   358.5 1701.81  361.591700.902  362.771700.804
   371.5 1700.67   382.1 1700.85   387.8 1702.05   397.5 1706.14   452.9 1709.77
     492 1715.67   560.5 1729.84   576.8 1735.04   593.1 1738.75   596.4 1740.42
#Mann= 6 ,-1 , 0
       0     .12       0  272.65     .06       0  302.98    .016       0
  361.59     .08       0  362.77    .045       0   382.1     .12       0
#XS Ineff= 2 , 0
          296.59 1711.34
Permanent Ineff=
       F       F
Bank Sta=362.77,382.1
XS Rating Curve= 0 ,0
Exp/Cntr=0.3,0.1

Type RM Length L Ch R = 1 ,13747.2 ,195.8,200.6,205.4
XS GIS Cut Line= 4
      2017006.51      273459.074      2016975.26      273627.477
     2017211.371      273830.602     2017249.566      273969.491
#Sta/Elev= 30
       0 1792.97    19.4 1782.15      42 1768.52    54.9 1761.45    67.9  1755.3
      84  1751.1      97 1744.49   113.1 1738.88   129.3  1738.1   135.7    1736
   148.7 1729.15   177.8    1712   194.2 1704.06   207.3 1702.15   213.9  1701.9
   264.11702.737   338.5 1703.96  354.691703.451   387.7 1705.89  405.46 1700.38
   420.4 1700.14     427 1700.31   430.3 1700.89   440.1 1704.45   476.2 1708.46
   489.3 1710.74   505.7 1715.09   574.4  1726.9   607.1 1740.67   626.8 1751.32
#Mann= 5 ,-1 , 0
       0     .12       0   264.1    .016       0  354.69     .12       0
  405.46    .045       0     427     .12       0
#XS Ineff= 2 , 0
          325.14 1713.38
Permanent Ineff=
       F       F
Bank Sta=405.46,427
XS Rating Curve= 0 ,0
Exp/Cntr=0.3,0.1

Type RM Length L Ch R = 1 ,13546.6 ,377.6,383.7,389.3
XS GIS Cut Line= 3
     2016822.018       273668.17     2017044.675      273962.441
      2017073.32       274074.42
#Sta/Elev= 30
       0 1723.21     3.3 1720.92     6.5 1719.84    16.3 1718.84    26.1 1712.31
    39.2 1706.86      49  1704.4    68.6  1703.8    91.4 1701.54   114.3 1702.07
   166.6 1700.94   225.3 1701.37   248.11700.579  284.171700.955   300.4  1700.6
  304.651699.815   309.9 1698.46   316.8 1696.79     320 1696.75   326.6 1696.96
   333.1 1698.65     356 1710.23   378.6 1724.81   388.3 1732.13   417.2 1757.16
   420.4 1760.86     430 1769.26   436.4 1777.09   462.1 1801.01   484.6 1819.65
#Mann= 6 ,-1 , 0
       0     .12       0   248.1     .06       0  284.17     .12       0
  304.65     .08       0   309.9    .045       0   333.1     .12       0
#XS Ineff= 2 , 0
          221.59  1716.2
Permanent Ineff=
       F       F
Bank Sta=309.9,333.1
XS Rating Curve= 0 ,0
Exp/Cntr=0.3,0.1

Type RM Length L Ch R = 1 ,13162.9 ,340.4,342.3,343.4
XS GIS Cut Line= 3
     2016700.087      273818.015     2016674.045      273989.456
     2016784.722      274243.363
#Sta/Elev= 30
       0 1740.38    32.7 1737.33   121.1 1725.39   127.6  1723.5   140.7  1715.6
   147.2 1713.96   170.1 1702.47   183.2 1697.31     193 1695.77  223.621694.098
   235.3 1690.33   251.6 1688.66   261.2  1690.2   271.2 1689.68   277.7 1691.03
   287.5 1691.57     294 1694.65   297.2 1699.96     307 1727.07   310.3 1734.54
   313.5 1739.81     320 1747.39   365.7  1780.6   391.7 1802.87  396.771805.042
   404.8 1806.15   421.1 1806.15  433.631814.095   443.9 1829.81   450.4 1835.78
#Mann= 6 ,-1 , 0
       0     .12       0  223.62     .08       0   261.2    .045       0
   277.7     .12       0  396.77    .016       0  433.63     .12       0
Bank Sta=261.2,277.7
XS Rating Curve= 0 ,0
Exp/Cntr=0.3,0.1

Type RM Length L Ch R = 1 ,12820.6 ,324,321,318.5
XS GIS Cut Line= 3
     2016363.715      273833.206     2016346.354      273993.797
     2016459.201      274323.658
#Sta/Elev= 30
       0 1750.08    77.5 1736.21   100.2 1731.47   113.1 1730.08     126 1727.26
  144.071725.302     168 1722.25   171.3 1720.84   174.6 1718.18   177.8 1714.58
   200.6 1692.61   207.1 1686.89   216.9 1679.72   220.2 1678.06   223.4 1677.49
   239.7 1675.67   246.2 1674.95     262 1675.88   278.8 1679.45   308.2 1681.35
   314.7 1682.73   324.4 1688.84   334.2 1692.04   337.5 1693.86   347.2 1701.57
   353.8 1703.25   392.9 1709.71   418.9 1717.26   487.4 1745.84   510.2 1756.83
#Mann= 4 ,-1 , 0
       0     .06       0  144.07     .12       0   239.7    .045       0
     262     .12       0
Bank Sta=239.7,262
XS Rating Curve= 0 ,0
Exp/Cntr=0.3,0.1

Type RM Length L Ch R = 1 ,12499.6 ,262.8,259.9,257.1
XS GIS Cut Line= 3
     2016046.875      273948.224     2016027.344      274087.113
     2016153.212      274341.019
#Sta/Elev= 30
       0 1734.42    16.3 1729.99   62.291720.629   101.1 1715.21  123.951713.352
     137 1712.87   146.8 1709.56   156.5 1707.86   163.1 1706.05   172.8 1700.73
   195.6 1684.26   205.4 1678.36   215.2 1673.66  222.28  1672.5     225 1672.22
   234.7 1672.08     251 1672.23  255.251672.511     264 1673.68   273.8  1674.1
   283.6  1675.5   290.1 1677.25   303.1 1683.38   319.4 1687.78   329.71689.747
   361.8 1695.96  389.731703.228   397.6 1705.89   410.6 1711.26   423.6 1717.76
#Mann= 9 ,-1 , 0
       0     .12       0   62.29     .06       0  123.95     .12       0
  222.28     .08       0     225    .045       0     251     .08       0
  255.25     .12       0   329.7     .06       0  389.73     .12       0
Bank Sta=225,251
XS Rating Curve= 0 ,0
Exp/Cntr=0.3,0.1

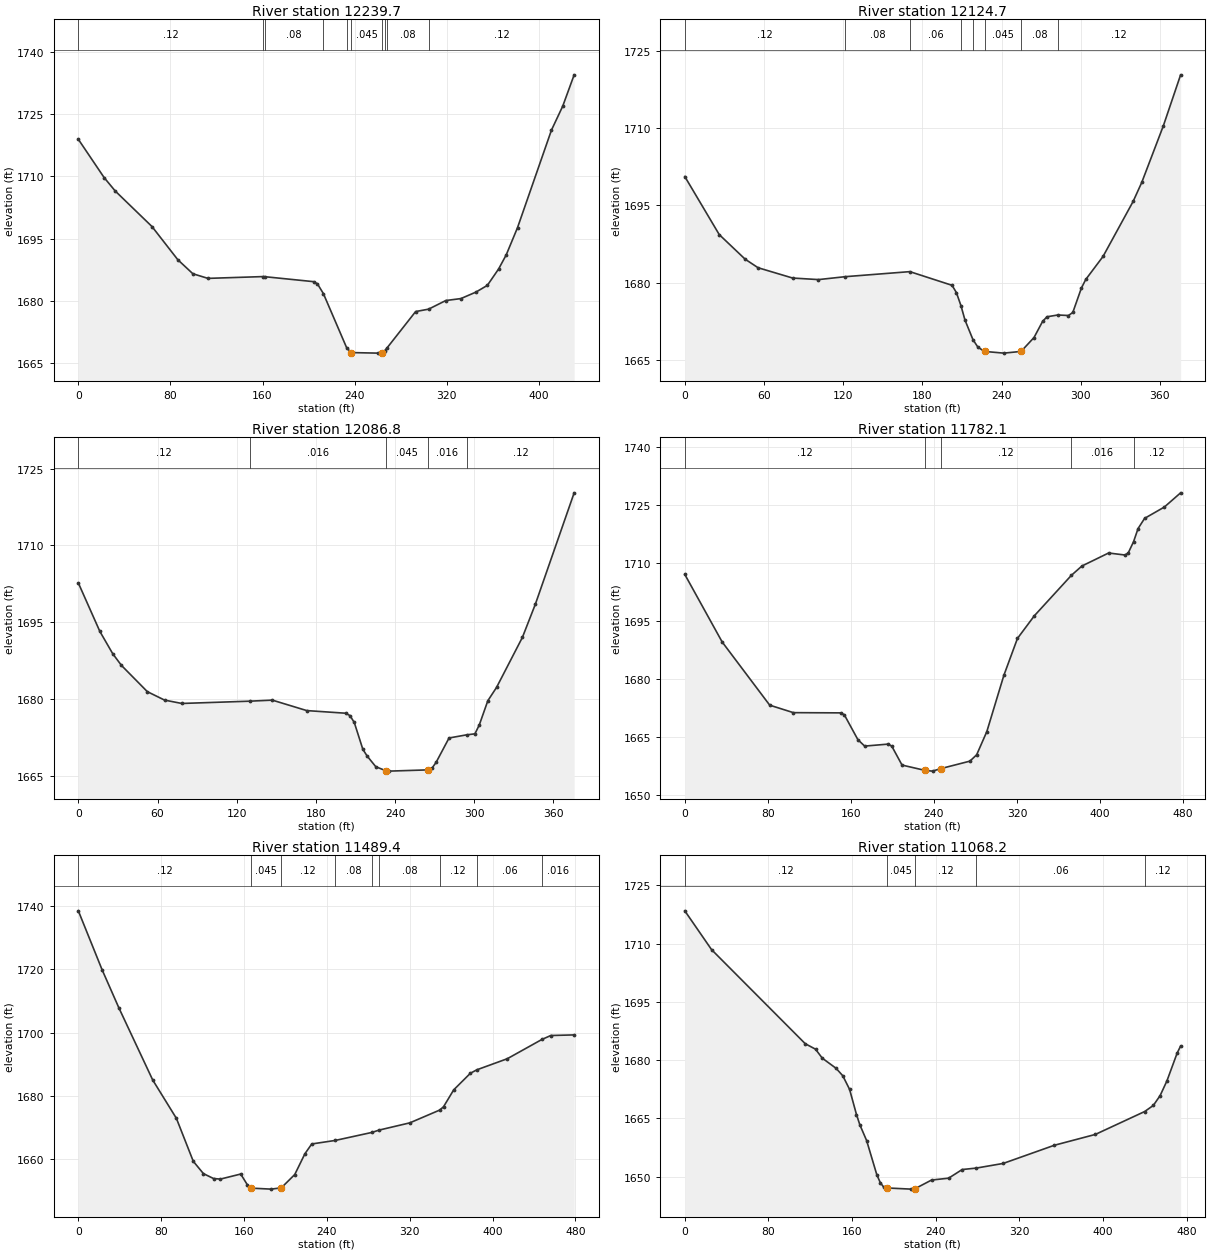
Type RM Length L Ch R = 1 ,12239.7 ,117.6,115,112.4
XS GIS Cut Line= 3
     2015766.927      274071.922     2015749.566      274156.557
     2015940.538      274443.015
#Sta/Elev= 30
       0 1718.91    22.4 1709.71      32 1706.49      64 1697.92    86.4 1689.95
    99.5 1686.57   112.6 1685.46  160.611685.892  162.261685.857   204.4 1684.67
   207.7 1684.15  212.891681.786  233.261668.656   237.2 1667.61   260.2 1667.48
   263.5 1667.56  266.14 1668.08  267.871668.633     293 1677.48  304.261678.055
   319.2 1680.13   332.3  1680.6   345.4 1682.16   355.3 1683.78   365.1 1687.73
   371.7 1691.12   381.5 1697.66     411 1721.13   420.8  1726.9   430.7 1734.42
#Mann= 10 ,-1 , 0
       0     .12       0  160.61     .06       0  162.26     .08       0
  212.89     .12       0  233.26     .08       0   237.2    .045       0
   263.5     .08       0  266.14     .12       0  267.87     .08       0
  304.26     .12       0
Bank Sta=237.2,263.5
XS Rating Curve= 0 ,0
Exp/Cntr=0.3,0.1

Type RM Length L Ch R = 1 ,12124.7 ,37.9,37.9,37.9
XS GIS Cut Line= 2
     2015593.316      274178.258     2015836.371      274464.717
#Sta/Elev= 30
       0  1700.6    26.1 1689.35    45.7 1684.59    55.5 1682.93    81.7 1680.93
   101.3 1680.63  121.691681.197  170.531682.172   202.5 1679.52   205.8 1678.11
  209.271675.564   212.3 1672.79  218.341668.997   222.1 1667.53   227.1 1666.71
   241.7 1666.38   254.8 1666.71   264.6  1669.4   271.1 1672.52   274.4 1673.42
  282.63 1673.77   290.7 1673.67     294 1674.26   300.5 1678.98   303.8 1680.65
   316.9 1685.11   339.7 1695.77   346.3 1699.49   362.6 1710.42   375.7 1720.31
#Mann= 8 ,-1 , 0
       0     .12       0  121.69     .08       0  170.53     .06       0
  209.27    .016       0  218.34     .08       0   227.1    .045       0
   254.8     .08       0  282.63     .12       0
Bank Sta=227.1,254.8
XS Rating Curve= 0 ,0
Exp/Cntr=0.3,0.1

Type RM Length L Ch R = 1 ,12086.8 ,291.5,304.8,317.8
XS GIS Cut Line= 2
     2015558.594       274195.62     2015801.649      274482.078
#Sta/Elev= 30
       0 1702.69    16.3 1693.25    26.1 1688.88    32.7 1686.61    52.3  1681.5
    65.3 1679.86    78.4  1679.2   129.71679.644     147 1679.85   173.1 1677.81
   202.5  1677.3   205.8 1676.84   209.1 1675.49   215.6 1670.25   218.9 1668.93
   225.4 1666.87   232.9  1666.1   235.2 1666.01   264.6 1666.25   267.9 1666.56
   271.1 1667.72   280.9 1672.47  294.261673.085   300.5 1673.28   303.8    1675
   310.3 1679.74   316.9 1682.33   336.5 1692.09   346.3 1698.55   375.7 1720.26
#Mann= 5 ,-1 , 0
       0     .12       0   129.7    .016       0   232.9    .045       0
   264.6    .016       0  294.26     .12       0
Bank Sta=232.9,264.6
XS Rating Curve= 0 ,0
Exp/Cntr=0.3,0.1

Type RM Length L Ch R = 1 ,11782.1 ,290.3,292.7,294.5
XS GIS Cut Line= 3
     2015400.173      274239.022     2015447.917      274631.818
      2015497.83      274696.922
#Sta/Elev= 30
       0 1707.09      36 1689.58    81.8  1673.2   104.6 1671.26   150.4  1671.2
   153.7  1670.7   166.8 1664.24   173.3 1662.59   196.2 1663.11   199.5 1662.53
   209.3 1657.67   231.6 1656.28   238.7  1656.1   246.6 1656.75   274.7 1658.69
   281.2 1660.34     291 1666.36   307.4 1680.93   320.5  1690.5   336.8 1696.38
  372.461706.856   382.6 1709.27   408.3 1712.64   424.1 1712.12   427.2 1712.64
  432.351715.566   436.7 1718.98     443 1721.62     462 1724.55   477.7 1728.24
#Mann= 5 ,-1 , 0
       0     .12       0   231.6    .045       0   246.6     .12       0
  372.46    .016       0  432.35     .12       0
Bank Sta=231.6,246.6
XS Rating Curve= 0 ,0
Exp/Cntr=0.3,0.1

Type RM Length L Ch R = 1 ,11489.4 ,434.7,421.1,407.2
XS GIS Cut Line= 3
     2015135.417      274271.574     2015144.097      274627.477
     2015230.903      274714.283
#Sta/Elev= 30
       0 1738.42    22.9 1719.86    39.2 1707.77    71.8 1685.06    94.7 1672.94
     111 1659.39   120.8  1655.5   130.6 1653.95   137.2 1653.78   156.8 1655.37
   163.3 1651.93   166.6 1650.93   186.2 1650.61     196 1651.02     209 1655.22
   218.8 1661.77   225.4 1664.86   248.2 1665.98  283.511668.502  290.391669.234
   320.1 1671.52  349.08 1675.57   352.7 1676.62   362.5 1681.94   378.6 1687.17
  384.791688.254   414.2 1691.75  447.641697.832   456.2 1699.08   478.8 1699.27
#Mann= 9 ,-1 , 0
       0     .12       0   166.6    .045       0     196     .12       0
   248.2     .08       0  283.51     .06       0  290.39     .08       0
  349.08     .12       0  384.79     .06       0  447.64    .016       0
Bank Sta=166.6,196
XS Rating Curve= 0 ,0
Exp/Cntr=0.3,0.1

Type RM Length L Ch R = 1 ,11068.2 ,441.2,457,472.1
XS GIS Cut Line= 3
     2014699.219      274349.699     2014705.729      274464.717
     2014924.913      274749.005
#Sta/Elev= 30
       0 1718.46    25.6 1708.46   115.2 1684.22     125 1682.81   131.5 1680.49
   144.6  1677.9   151.1 1675.96   157.6 1672.45   164.2 1665.97   167.4 1663.33
   173.9 1659.26   183.7 1650.41     187  1648.4   190.3 1647.25   193.5 1647.05
   216.4 1646.75     220 1646.84     236 1649.09   252.3 1649.57   265.3  1651.8
  278.771652.172   304.5 1653.37   353.4 1658.05   392.6 1660.84  439.831666.746
   448.1 1668.32   454.6 1670.85   461.1 1674.64   470.9 1681.82   474.2 1683.63
#Mann= 5 ,-1 , 0
       0     .12       0   193.5    .045       0     220     .12       0
  278.77     .06       0  439.83     .12       0
Bank Sta=193.5,220
XS Rating Curve= 0 ,0
Exp/Cntr=0.3,0.1