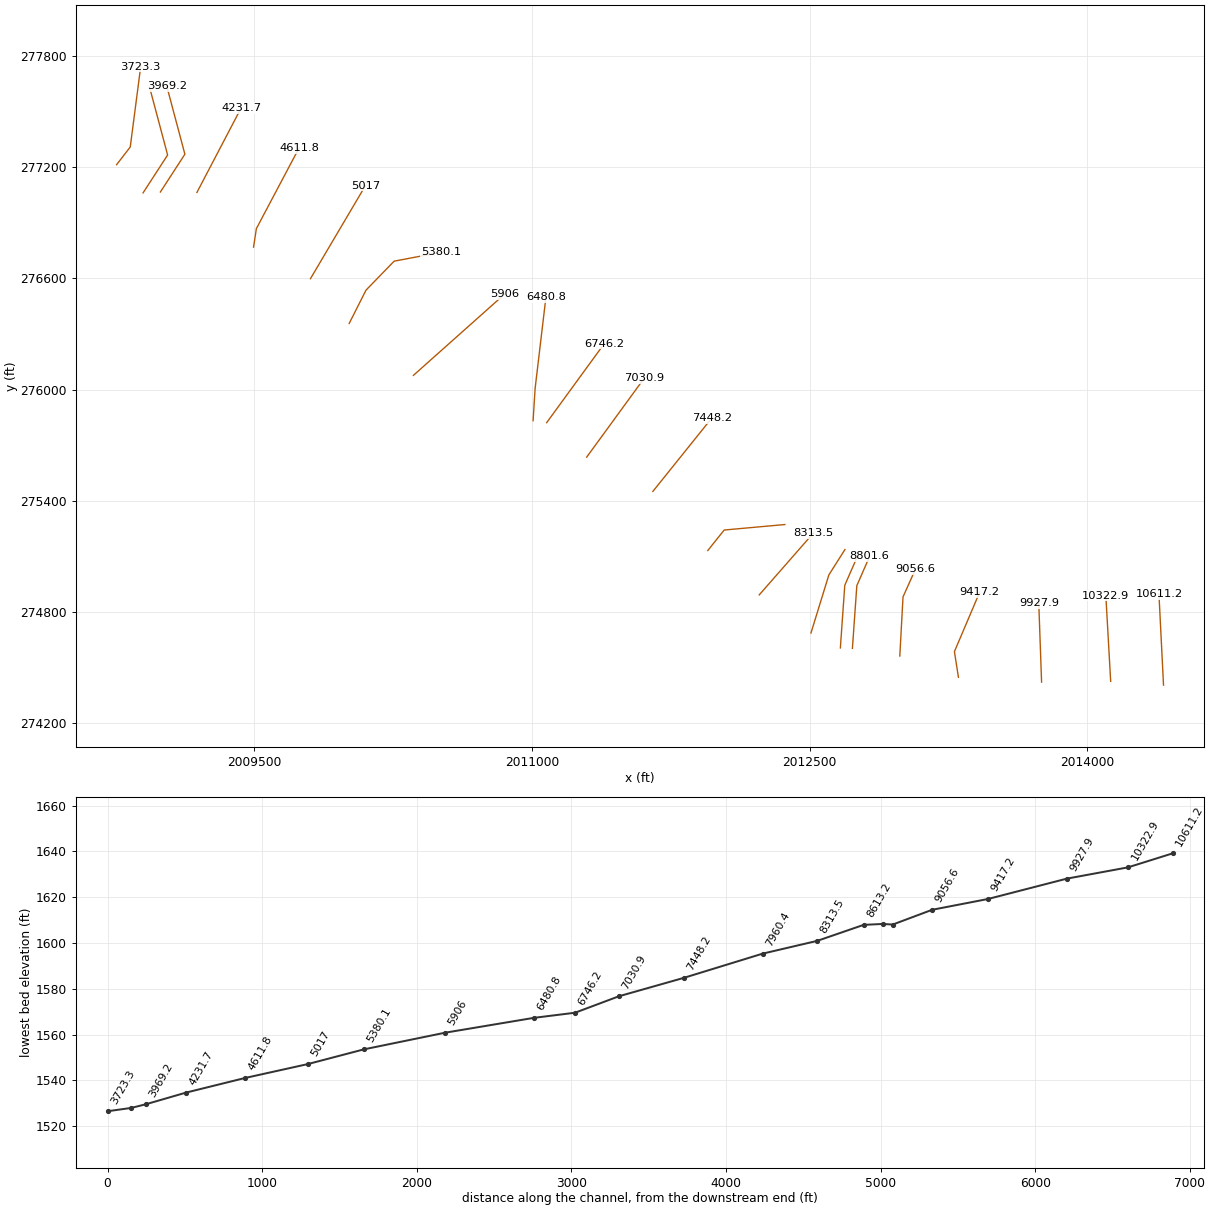
HEC-RAS study LAURELCK.prj: LAURELCK

--- LAURELCK.g01 (geometry) --- (continued)

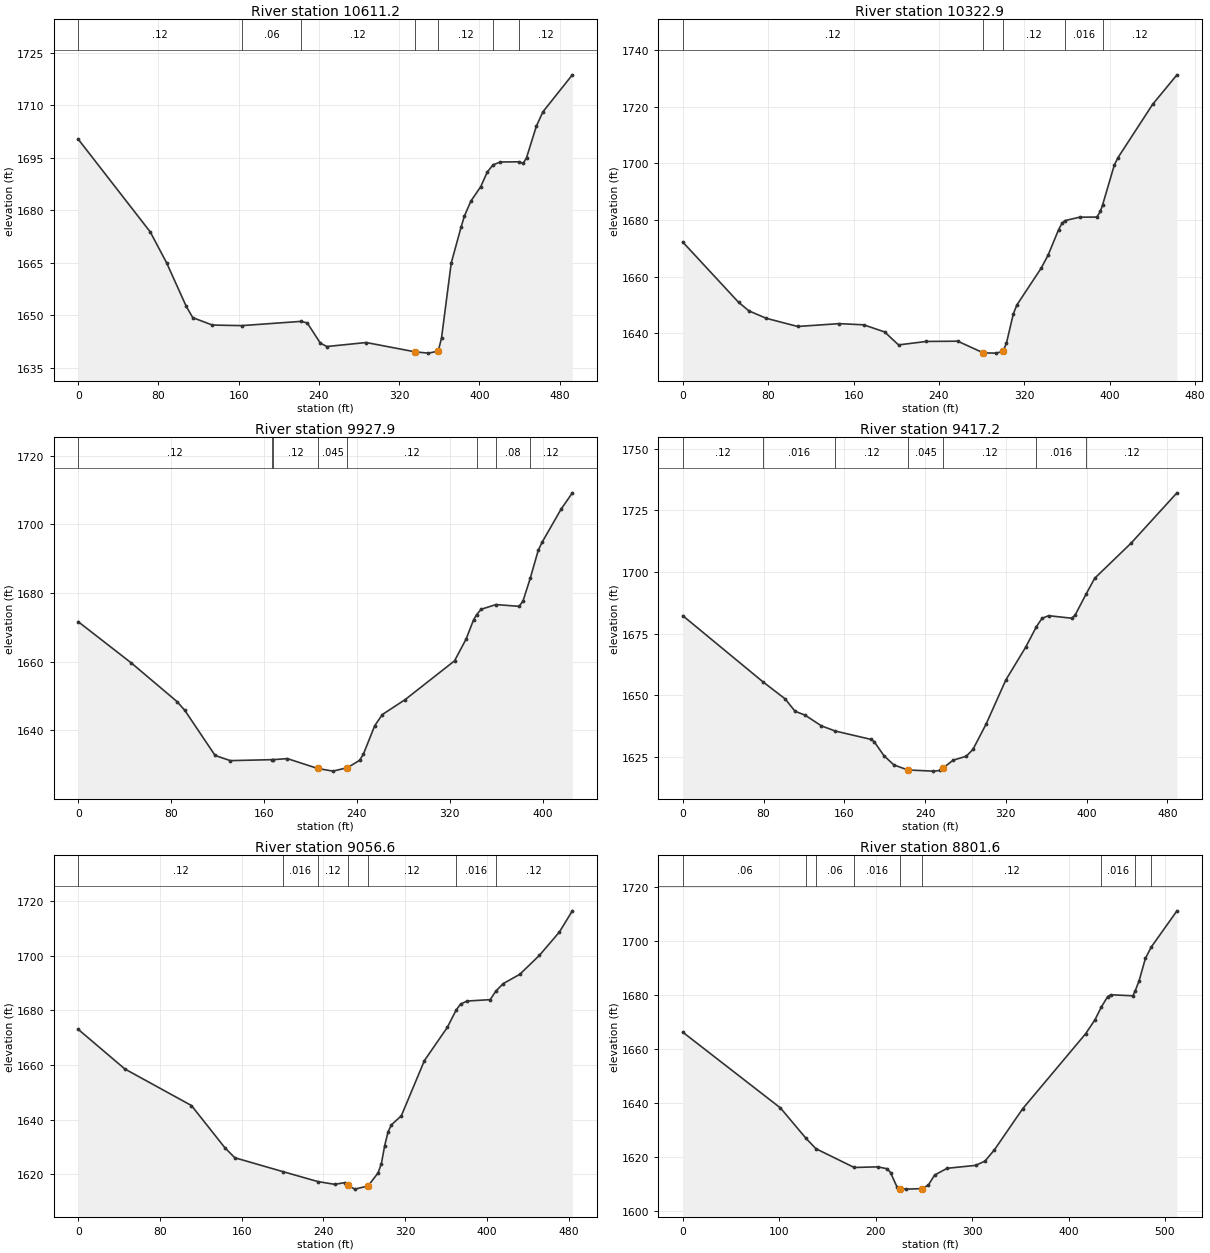
Type RM Length L Ch R = 1 ,10611.2 ,288.5,288.3,288.2
XS GIS Cut Line= 2
     2014411.862      274405.149     2014387.123      274897.337
#Sta/Elev= 30
       0 1700.26    71.8 1673.78    88.1 1664.96   107.7 1652.52   114.2 1649.28
   133.8 1647.16  163.04    1647  222.371648.216   228.4 1647.77   241.5 1641.98
     248 1641.03   287.2 1642.17   336.2 1639.49   349.2 1639.14     359  1639.7
   362.3 1643.45     372  1664.9   381.8 1675.13   385.1 1678.29   391.6 1682.59
   401.4  1686.7     408 1690.92  413.831692.952     421 1693.76  439.821693.809
   443.8 1693.36   447.1 1694.98   456.9    1704   463.4 1708.08   492.8 1718.66
#Mann= 7 ,-1 , 0
       0     .12       0  163.04     .06       0  222.37     .12       0
   336.2    .045       0     359     .12       0  413.83    .016       0
  439.82     .12       0
Bank Sta=336.2,359
XS Rating Curve= 0 ,0
Exp/Cntr=0.3,0.1

Type RM Length L Ch R = 1 ,10322.9 ,395.9,394.9,393.2
XS GIS Cut Line= 2
     2014126.302      274425.654      2014100.26      274887.894
#Sta/Elev= 30
       0 1672.18    52.2 1650.98      62 1647.92    78.2 1645.32   107.6 1642.44
   146.7 1643.44   169.5 1643.02   189.1 1640.51   202.1 1635.94   228.2 1637.16
   257.6 1637.25   281.6 1633.12   293.4 1633.04     300 1633.66   303.2 1636.52
   309.7 1646.92     313 1650.02   335.8 1663.02   342.3 1667.63   352.1 1676.58
   355.4 1678.92  358.291679.778   371.7 1680.97     388 1681.02   391.2 1682.99
  393.291685.257   404.3 1699.35   407.6 1701.88   440.2 1720.76     463 1731.17
#Mann= 5 ,-1 , 0
       0     .12       0   281.6    .045       0     300     .12       0
  358.29    .016       0  393.29     .12       0
Bank Sta=281.6,300
XS Rating Curve= 0 ,0
Exp/Cntr=0.3,0.1

Type RM Length L Ch R = 1 ,9927.9  ,520.5,510.8,501.2
XS GIS Cut Line= 2
     2013753.038      274421.314     2013737.847      274846.661
#Sta/Elev= 30
       0 1671.66    45.8 1659.62    85.1 1648.38    91.7 1645.87   117.9 1632.68
     131 1631.18  166.481631.457  167.781631.467   180.1 1631.77   206.3 1628.89
   219.4 1628.12   231.9 1629.13   242.3 1631.26   245.6 1633.07   255.4 1641.38
   261.9  1644.6   281.6 1648.97   324.1 1660.26     334 1666.56   340.5 1672.19
   343.11673.703     347 1675.28  359.781676.656   379.8 1676.14   383.1 1677.72
  389.331684.331   396.2 1692.46   399.4 1694.75   415.8 1704.41   425.6 1709.22
#Mann= 8 ,-1 , 0
       0     .12       0  166.48     .06       0  167.78     .12       0
   206.3    .045       0   231.9     .12       0   343.1    .016       0
  359.78     .08       0  389.33     .12       0
Bank Sta=206.3,231.9
XS Rating Curve= 0 ,0
Exp/Cntr=0.3,0.1

Type RM Length L Ch R = 1 ,9417.2  ,352.5,360.6,367.7
XS GIS Cut Line= 3
     2013303.819      274447.356     2013282.118      274586.245
     2013418.837      274907.425
#Sta/Elev= 30
       0 1682.28   79.361655.466   101.3 1648.56   111.2 1643.51     121 1641.97
   137.3 1637.59  151.021635.489   186.2 1632.12   189.5 1631.24   199.3 1625.47
   209.1 1621.74     223 1619.69   248.2 1619.22   254.8 1619.48     258 1620.54
   267.8 1623.65   280.8 1625.26   287.4    1628   300.4 1638.23     320 1656.18
   339.6 1669.44  350.371677.857   355.9 1681.21   362.4  1682.3   385.2 1681.27
   388.5 1682.39  399.571691.065   408.1 1697.48     444 1711.67   489.6 1732.15
#Mann= 7 ,-1 , 0
       0     .12       0   79.36    .016       0  151.02     .12       0
     223    .045       0     258     .12       0  350.37    .016       0
  399.57     .12       0
Bank Sta=223,258
XS Rating Curve= 0 ,0
Exp/Cntr=0.3,0.1

Type RM Length L Ch R = 1 ,9056.6  ,255.3,255,254.5
XS GIS Cut Line= 3
     2012986.979      274562.373      2013004.34      274881.383
     2013071.614      275031.123
#Sta/Elev= 30
       0 1673.03    45.6 1658.53   110.8 1645.13   143.4 1629.72   153.2 1626.01
   200.11620.943  234.721617.259     251 1616.27   260.8 1616.88   263.7 1615.95
   270.6 1614.51   283.6 1615.65   293.4 1620.43   296.7 1623.88   299.9 1630.42
   303.2 1635.45   306.4 1638.03   316.2 1641.37   338.8  1661.6   361.3 1673.81
  369.861680.121   374.2 1682.29   380.6  1683.4   403.2 1683.92  408.751687.072
     416 1689.81   432.1 1693.18   451.4 1700.16   470.8 1708.64   483.6 1716.45
#Mann= 7 ,-1 , 0
       0     .12       0   200.1    .016       0  234.72     .12       0
   263.7    .045       0   283.6     .12       0  369.86    .016       0
  408.75     .12       0
Bank Sta=263.7,283.6
XS Rating Curve= 0 ,0
Exp/Cntr=0.3,0.1

Type RM Length L Ch R = 1 ,8801.6  ,65.2,65.2,65.2
XS GIS Cut Line= 3
     2012730.903      274603.606     2012754.774      274942.147
     2012824.219      275100.568
#Sta/Elev= 30
       0 1666.12   101.2 1638.11  127.821626.816  138.05 1623.01  177.681616.074
   202.3  1616.3   212.1 1615.58   215.4 1614.16   221.9 1609.02   225.2 1608.29
   231.7 1608.06     248 1608.25   254.5 1609.52   261.1 1613.27   274.1 1615.77
   303.5 1616.84   313.3 1618.42   323.1  1622.6   352.4  1637.8   417.7 1665.56
   427.5  1670.8  433.881675.383   440.6 1679.33   443.8 1679.98   466.7  1679.6
  469.11 1681.43   473.2 1685.22   479.7 1693.46  485.781697.649   512.4 1711.04
#Mann= 9 ,-1 , 0
       0     .06       0  127.82     .12       0  138.05     .06       0
  177.68    .016       0   225.2    .045       0     248     .12       0
  433.88    .016       0  469.11     .08       0  485.78     .12       0
Bank Sta=225.2,248
XS Rating Curve= 0 ,0
Exp/Cntr=0.3,0.1

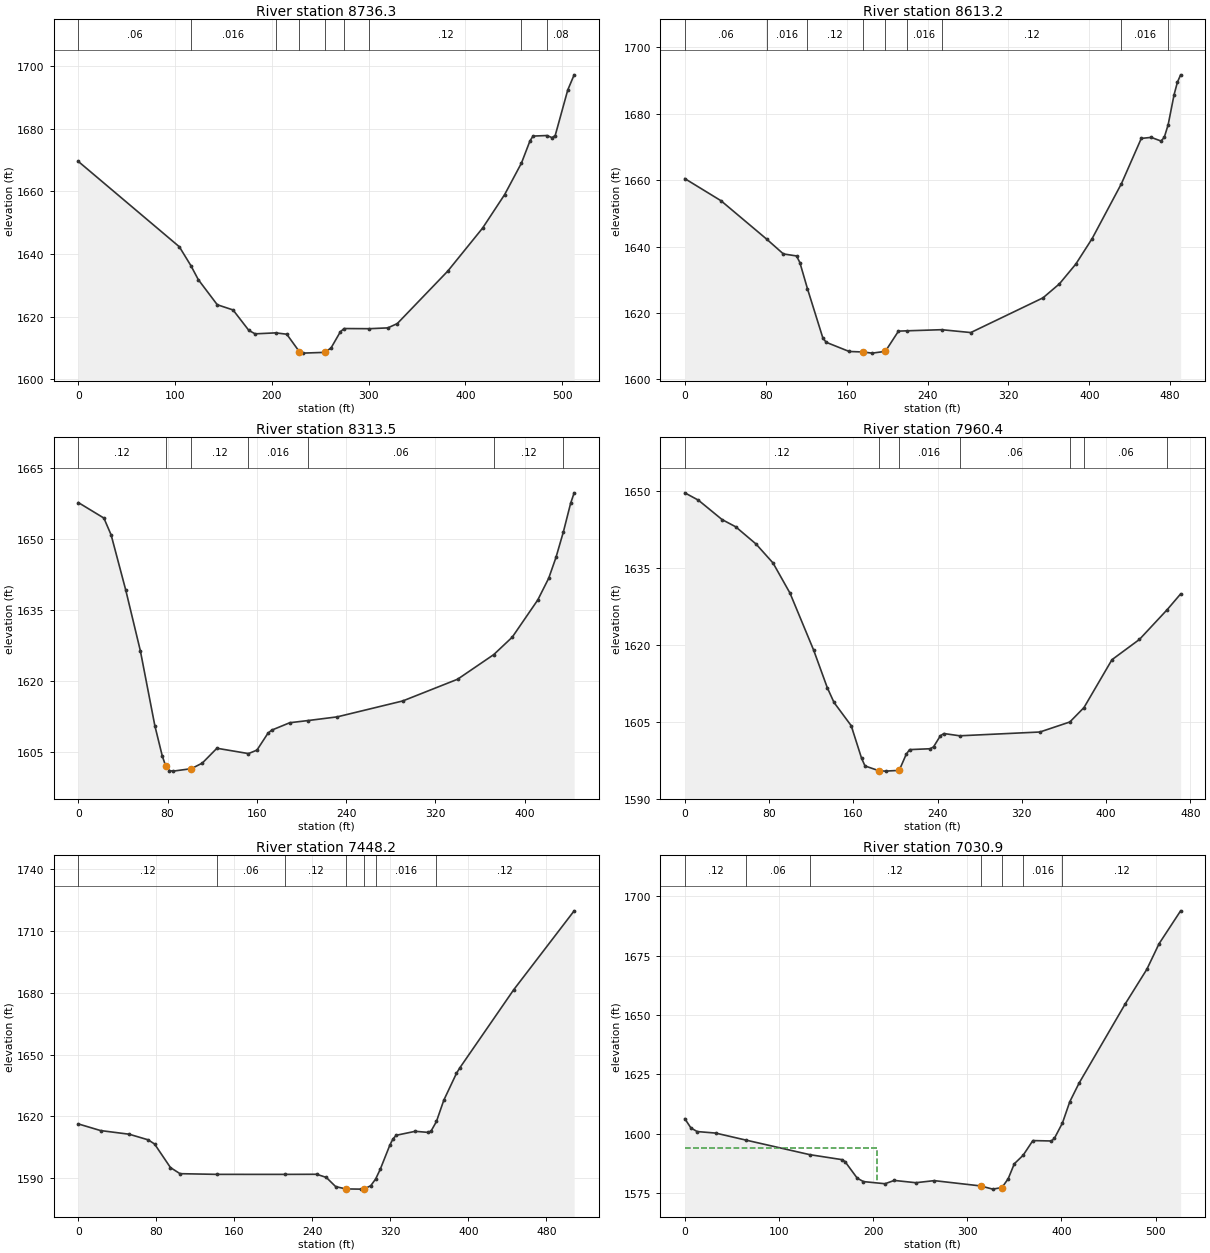
Type RM Length L Ch R = 1 ,8736.3  ,128.2,123.1,117.5
XS GIS Cut Line= 3
     2012665.798      274605.776      2012689.67      274944.318
     2012759.114      275102.738
#Sta/Elev= 30
       0 1669.53   104.4 1642.28  116.281636.277     124 1631.78   143.6 1623.77
   159.9 1622.11   176.2 1615.58   182.7 1614.48  203.94 1614.79   215.4 1614.36
   228.4 1608.79   231.7 1608.32   254.5 1608.56   261.1 1609.94   270.8 1615.14
  274.641616.172  300.751616.122   319.8 1616.38   329.6 1617.75   381.8 1634.52
   417.7 1648.22   440.6 1658.97  457.931669.011   466.7 1676.07   469.9 1677.63
  484.131677.805   489.5 1677.15   492.8  1677.8   505.8 1692.37   512.4 1697.19
#Mann= 9 ,-1 , 0
       0     .06       0  116.28    .016       0  203.94     .12       0
   228.4    .045       0   254.5     .12       0  274.64    .016       0
  300.75     .12       0  457.93    .016       0  484.13     .08       0
Bank Sta=228.4,254.5
XS Rating Curve= 0 ,0
Exp/Cntr=0.3,0.1

Type RM Length L Ch R = 1 ,8613.2  ,308.7,299.7,290.1
XS GIS Cut Line= 3
     2012506.914      274686.399     2012603.717      275000.071
     2012690.508       275136.92
#Sta/Elev= 30
       0 1660.43    35.8 1653.77   81.111642.176    97.5 1637.76   110.5 1637.16
   113.8 1635.16  121.291627.305   136.5  1612.5   139.8 1611.18   162.5 1608.42
   176.2 1608.26   185.3 1607.92   198.3 1608.45   211.3 1614.54  219.991614.637
  253.961614.969   282.8 1614.11   354.2 1624.55   370.4 1628.75   386.6 1634.69
   402.8 1642.38  431.781658.918   451.4 1672.52   461.2 1672.83   470.9 1671.74
   474.1 1672.82  477.971676.628   483.8 1685.63   487.1 1689.42   490.3 1691.65
#Mann= 9 ,-1 , 0
       0     .06       0   81.11    .016       0  121.29     .12       0
   176.2    .045       0   198.3     .12       0  219.99    .016       0
  253.96     .12       0  431.78    .016       0  477.97     .12       0
Bank Sta=176.2,198.3
XS Rating Curve= 0 ,0
Exp/Cntr=0.3,0.1

Type RM Length L Ch R = 1 ,8313.5  ,370.2,353,335.6
XS GIS Cut Line= 2
      2012227.43      274892.234     2012520.399      275226.436
#Sta/Elev= 30
       0 1657.76    22.9 1654.48    29.4 1650.91    42.5 1639.24    55.6 1626.39
    68.6 1610.53    75.2 1604.18    78.4 1601.95    81.7 1601.04      85 1600.94
   101.3 1601.46   111.1 1602.64   124.2 1605.78  152.49 1604.65   160.1 1605.39
   169.9 1608.94   173.2  1609.6   189.5 1611.18  205.841611.639     232 1612.42
   290.8 1615.79   339.9 1620.38  372.331625.594   388.9 1629.28   411.8 1637.16
   421.6 1641.76   428.1 1646.15  434.76 1651.58   441.2 1657.57   444.4 1659.82
#Mann= 7 ,-1 , 0
       0     .12       0    78.4    .045       0   101.3     .12       0
  152.49    .016       0  205.84     .06       0  372.33     .12       0
  434.76    .016       0
Bank Sta=78.4,101.3
XS Rating Curve= 0 ,0
Exp/Cntr=0.3,0.1

Type RM Length L Ch R = 1 ,7960.4  ,493.5,512.2,530
XS GIS Cut Line= 3
     2011949.623      275131.712     2012038.164      275242.389
     2012365.885      275272.008
#Sta/Elev= 30
       0 1649.56    12.9 1648.13    35.4 1644.35    48.3 1642.95    67.6  1639.6
    83.8 1635.89    99.9 1630.02   122.4  1618.9   135.3 1611.61   141.7 1608.73
     158 1604.21   167.8  1597.9   171.1 1596.37   184.4 1595.43   190.6 1595.36
   203.6 1595.51   210.2 1598.62   213.4 1599.55     233 1599.72   236.2 1600.09
   242.7 1602.25     246 1602.68  261.081602.241   337.2 1602.98   365.61604.931
  379.031607.737   405.6 1617.06   431.7 1621.01  458.141626.828   470.8 1629.87
#Mann= 7 ,-1 , 0
       0     .12       0   184.4    .045       0   203.6    .016       0
  261.08     .06       0   365.6     .12       0  379.03     .06       0
  458.14     .12       0
Bank Sta=184.4,203.6
XS Rating Curve= 0 ,0
Exp/Cntr=0.3,0.1

Type RM Length L Ch R = 1 ,7448.2  ,416,417.4,418
XS GIS Cut Line= 2
     2011652.748      275450.722     2011971.354      275847.095
#Sta/Elev= 30
       0 1616.38    22.8 1613.16    52.2 1611.38    71.7 1608.65    78.2 1606.63
    94.5  1595.2   104.3 1592.23  141.94  1591.9   211.9 1591.89   244.5 1591.94
   254.3 1590.43     264 1585.94   274.5 1584.83   289.5 1584.73   293.4 1584.86
   299.9 1586.38  304.881589.567   309.7 1594.38   319.5 1606.04   322.7 1609.07
     326 1610.86   345.6  1612.8   358.6 1612.28   361.8 1612.89  367.33 1617.56
   374.9 1627.92   387.9 1640.96   391.2 1643.53   446.6 1681.53   508.6 1719.83
#Mann= 7 ,-1 , 0
       0     .12       0  141.94     .06       0   211.9     .12       0
   274.5    .045       0   293.4     .12       0  304.88    .016       0
  367.33     .12       0
Bank Sta=274.5,293.4
XS Rating Curve= 0 ,0
Exp/Cntr=0.3,0.1

Type RM Length L Ch R = 1 ,7030.9  ,284.6,284.6,284.7
XS GIS Cut Line= 2
     2011295.139      275635.724     2011605.469      276061.071
#Sta/Elev= 30
       0 1606.37     6.5 1602.48    13.1 1600.96    32.7 1600.32   65.111597.345
  132.791591.233   166.8 1589.15   170.1 1588.34   183.1 1581.35   189.7 1579.91
   212.6 1579.01   222.4  1580.4   245.3 1579.44   264.9 1580.31     314 1578.09
     327 1576.74   336.8 1577.41   343.4 1581.11   349.9  1587.4  359.27 1590.99
   369.6 1597.16   389.2 1596.99   392.4 1598.04  401.031604.581   408.8  1613.5
   418.6 1621.28   467.7 1654.67   490.6 1669.19   503.6 1679.96   526.5  1693.8
#Mann= 7 ,-1 , 0
       0     .12       0   65.11     .06       0  132.79     .12       0
     314    .045       0   336.8     .12       0  359.27    .016       0
  401.03     .12       0
#XS Ineff= 2 , 0
          204.55 1593.89
Permanent Ineff=
       F       F
Bank Sta=314,336.8
XS Rating Curve= 0 ,0
Exp/Cntr=0.3,0.1

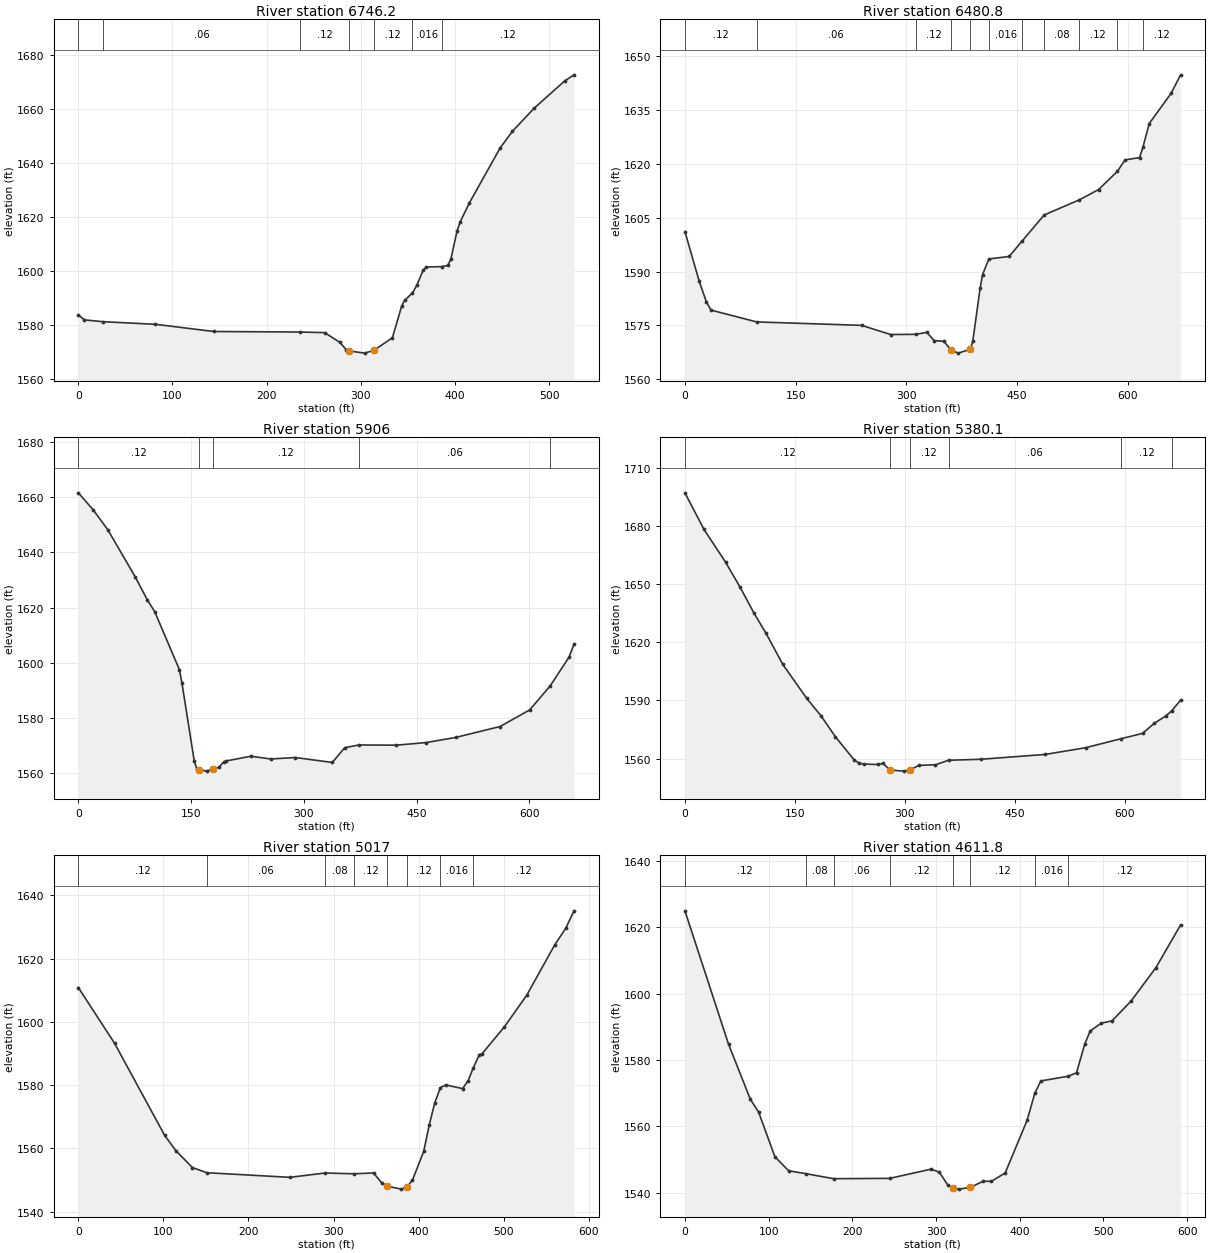
Type RM Length L Ch R = 1 ,6746.2  ,253.5,265.5,276.8
XS GIS Cut Line= 2
     2011078.993      275821.922     2011389.323      276247.269
#Sta/Elev= 30
       0 1583.65     6.5 1581.85   26.321581.177    81.8 1580.22   143.9 1577.55
  235.49 1577.35   261.6 1577.13     278 1573.48   284.5 1570.79   287.8 1570.33
   304.1 1569.53     314 1570.56   333.6 1575.24   343.4 1586.92   346.6 1589.12
  354.871591.793   359.7 1594.81   366.3 1600.27   369.6 1601.47  386.041601.589
   392.4 1602.05   395.7 1604.39   402.2 1614.74   405.5 1618.12   415.3 1625.19
     448 1645.58   461.1 1651.77     484 1660.27   516.7 1670.46   526.5 1672.69
#Mann= 7 ,-1 , 0
       0     .12       0   26.32     .06       0  235.49     .12       0
   287.8    .045       0     314     .12       0  354.87    .016       0
  386.04     .12       0
Bank Sta=287.8,314
XS Rating Curve= 0 ,0
Exp/Cntr=0.3,0.1

Type RM Length L Ch R = 1 ,6480.8  ,590.6,574.8,557.1
XS GIS Cut Line= 3
     2011005.612      275832.667     2011016.463      276006.278
     2011075.087      276500.307
#Sta/Elev= 30
       0 1601.09    19.3 1587.34      29 1581.57    35.4 1579.26   97.121575.981
   239.4 1575.02   278.7 1572.47  312.411572.527   327.8 1573.07   337.6 1570.76
   350.7  1570.6   360.9 1568.07   370.3  1567.3   386.7 1568.39     390 1570.77
   399.8 1585.33   403.1  1589.1  411.691593.501   439.1 1594.18  456.891598.521
  486.641605.732  533.79 1609.89   560.2 1612.78  585.641617.828   596.2 1621.04
   615.8 1621.68   620.3 1624.54   628.9 1631.15   658.4 1639.53   671.4  1644.7
#Mann= 11 ,-1 , 0
       0     .12       0   97.12     .06       0  312.41     .12       0
   360.9    .045       0   386.7     .12       0  411.69    .016       0
  456.89     .06       0  486.64     .08       0  533.79     .12       0
  585.64    .016       0   620.3     .12       0
Bank Sta=360.9,386.7
XS Rating Curve= 0 ,0
Exp/Cntr=0.3,0.1

Type RM Length L Ch R = 1 ,5906    ,523.6,525.9,528
XS GIS Cut Line= 2
     2010358.941       276077.13     2010851.562      276515.498
#Sta/Elev= 30
       0 1661.56    19.7 1655.42    39.4 1648.11    75.5 1631.21    91.9 1622.76
   101.7 1618.48   134.5 1597.51   137.8 1592.77   154.2 1564.46   157.5 1561.73
   160.8 1561.38   170.6 1560.81   179.2 1561.59     187 1562.21   193.6  1564.2
   196.8 1564.51   229.6  1566.2   255.9 1565.21   288.7 1565.73   337.9 1563.95
   354.3 1569.28  373.241570.279   423.2 1570.21   462.6 1571.15     502 1573.01
     561 1576.96   600.4 1582.97  627.61 1591.64   652.9 1602.13   659.4  1606.8
#Mann= 5 ,-1 , 0
       0     .12       0   160.8    .045       0   179.2     .12       0
  373.24     .06       0  627.61     .12       0
Bank Sta=160.8,179.2
XS Rating Curve= 0 ,0
Exp/Cntr=0.3,0.1

Type RM Length L Ch R = 1 ,5380.1  ,358.2,363.2,367.8
XS GIS Cut Line= 4
     2010011.719      276357.078     2010102.864      276537.199
     2010254.774      276693.449      2010506.51      276741.193
#Sta/Elev= 30
       0 1697.21      26 1678.31    55.4 1661.42    74.9  1648.7    94.4 1634.97
   110.7 1624.63   133.5 1608.61     166 1591.14   185.6 1582.06   205.1 1571.34
   231.1 1559.15   237.6  1557.7   244.2 1557.15   263.7 1556.95   270.2 1557.49
   279.9 1554.06   299.4 1553.52   307.1 1554.16     319 1556.51   341.7  1556.8
  359.541559.136   403.5 1559.64   491.2 1562.14   546.3  1565.6  594.981570.289
   624.1    1573   640.3 1578.28   656.6 1582.19  664.141584.816     676 1590.18
#Mann= 6 ,-1 , 0
       0     .12       0   279.9    .045       0   307.1     .12       0
  359.54     .06       0  594.98     .12       0  664.14    .016       0
Bank Sta=279.9,307.1
XS Rating Curve= 0 ,0
Exp/Cntr=0.3,0.1

Type RM Length L Ch R = 1 ,5017    ,404,405.1,406.1
XS GIS Cut Line= 2
     2009802.615      276598.923     2010099.294      277100.476
#Sta/Elev= 30
       0 1610.86    42.6 1593.23   101.5 1564.08   114.6 1559.27   134.2 1553.89
   151.11552.272   248.8 1550.81  289.921552.182  324.24 1551.93     347  1552.2
   356.8 1549.02   363.4 1547.99   379.8 1547.08   386.3  1547.8   392.8 1549.95
     406 1559.02   412.5 1567.39     419 1574.37  425.571579.203   432.1 1580.03
   451.8 1578.89   458.3 1581.43  464.131585.363   471.4 1589.61   474.7 1589.95
   500.9 1598.45   527.1 1608.42   559.8 1624.26   572.9 1629.58   582.7 1635.13
#Mann= 8 ,-1 , 0
       0     .12       0   151.1     .06       0  289.92     .08       0
  324.24     .12       0   363.4    .045       0   386.3     .12       0
  425.57    .016       0  464.13     .12       0
Bank Sta=363.4,386.3
XS Rating Curve= 0 ,0
Exp/Cntr=0.3,0.1

Type RM Length L Ch R = 1 ,4611.8  ,379.9,380.2,380.3
XS GIS Cut Line= 3
     2009495.226      276769.404     2009510.417      276869.231
     2009740.451      277303.258
#Sta/Elev= 30
       0 1625.02    52.1 1584.76    78.2 1568.12      88 1564.28   107.5  1550.8
   123.9 1546.56  144.311545.686  177.741544.172   244.61544.267   294.2 1547.06
     304 1546.13   313.8 1542.34   320.4 1541.26   326.9 1541.02   340.7 1541.52
   356.4 1543.41   366.2 1543.38   382.6  1545.9   408.8 1561.79  418.061570.016
   425.2 1573.68  458.091575.099   467.8 1576.14   477.6 1584.74   484.1 1588.73
   497.2 1591.08   510.3 1591.82   533.2 1597.85   562.7 1607.89   592.2 1620.79
#Mann= 8 ,-1 , 0
       0     .12       0  144.31     .08       0  177.74     .06       0
   244.6     .12       0   320.4    .045       0   340.7     .12       0
  418.06    .016       0  458.09     .12       0
Bank Sta=320.4,340.7
XS Rating Curve= 0 ,0
Exp/Cntr=0.3,0.1

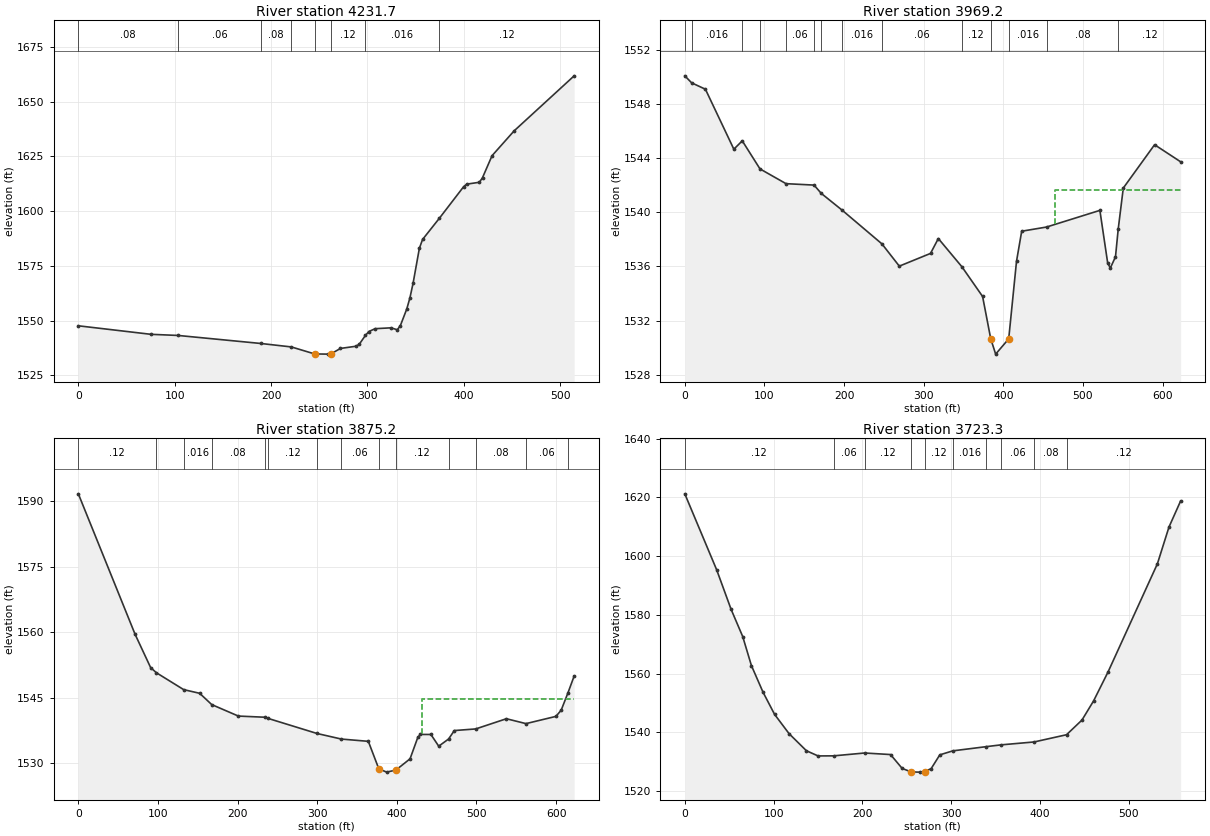
Type RM Length L Ch R = 1 ,4231.7  ,245.1,262.4,278.6
XS GIS Cut Line= 2
     2009189.236      277064.543     2009427.951      277520.272
#Sta/Elev= 30
       0 1547.61    75.4 1543.71  103.551543.195  189.531539.521  221.081537.944
   245.2 1534.75   258.9 1534.66   262.2  1534.8     272 1537.26   288.4 1538.28
   291.6 1539.23  297.881543.196   301.5    1545     308 1546.29   324.4 1546.68
     331  1545.8   334.2 1547.74   340.8 1555.28   344.1 1560.41   347.4 1567.16
   353.9 1583.06   357.2 1587.07  374.721596.806   399.8 1611.18     403 1612.35
   416.2 1613.21   419.4 1615.31   429.3 1625.36   452.2  1636.7   514.5 1661.86
#Mann= 8 ,-1 , 0
       0     .08       0  103.55     .06       0  189.53     .08       0
  221.08     .12       0   245.2    .045       0   262.2     .12       0
  297.88    .016       0  374.72     .12       0
Bank Sta=245.2,262.2
XS Rating Curve= 0 ,0
Exp/Cntr=0.3,0.1

Type RM Length L Ch R = 1 ,3969.2  ,93.8,94,93.9
XS GIS Cut Line= 3
     2008991.753      277066.713     2009124.132      277270.706
     2009026.476       277637.46
#Sta/Elev= 30
       0 1550.08    8.611549.561    25.9 1549.09    61.6 1544.66   72.181545.277
   94.441543.203  127.131542.113  162.341542.008  171.391541.395  197.561540.157
   247.61537.663   269.4 1536.02   308.6 1536.96   318.4 1538.06  348.071535.969
     374 1533.78   384.2 1530.66   390.4 1529.52   406.8 1530.65   416.6 1536.38
   423.1  1538.6  454.311538.909   521.3 1540.14   531.1 1536.25   534.4 1535.88
   540.9 1536.71  544.321538.757   550.7 1541.79     590 1544.99   622.7 1543.73
#Mann= 14 ,-1 , 0
       0     .06       0    8.61    .016       0   72.18     .08       0
   94.44    .016       0  127.13     .06       0  162.34     .08       0
  171.39     .12       0  197.56    .016       0   247.6     .06       0
  348.07     .12       0   384.2    .045       0   406.8    .016       0
  454.31     .08       0  544.32     .12       0
#XS Ineff= 2 , 0
                          465.34         1541.66
Permanent Ineff=
       F       F
Bank Sta=384.2,406.8
XS Rating Curve= 0 ,0
Exp/Cntr=0.3,0.1

Type RM Length L Ch R = 1 ,3875.2  ,161.1,151.9,143.1
XS GIS Cut Line= 3
     2008898.437      277062.373     2009030.816      277266.366
      2008933.16       277633.12
#Sta/Elev= 30
       0 1591.74    71.3 1559.53    90.8 1551.91   98.061550.722   132.31546.853
   152.4 1546.01  167.521543.425     201 1540.79  234.291540.525  237.941540.275
  299.771536.798  330.331535.521   364.2    1535   377.3 1528.73   387.1 1527.94
   398.8 1528.41   416.6 1530.99   426.4 1535.93   429.7 1536.58   442.8 1536.57
   452.6 1533.89  464.981535.528   472.2 1537.47  499.031537.841   537.6 1540.18
   562.2 1539.06   599.8 1540.72   606.4 1542.14  614.72 1546.02   622.7 1549.97
#Mann= 14 ,-1 , 0
       0     .12       0   98.06     .08       0   132.3    .016       0
  167.52     .08       0  234.29    .016       0  237.94     .12       0
  299.77     .08       0  330.33     .06       0   377.3    .045       0
   398.8     .12       0  464.98    .016       0  499.03     .08       0
   562.2     .06       0  614.72     .12       0
#XS Ineff= 2 , 0
                          431.53         1544.76
Permanent Ineff=
       F       F
Bank Sta=377.3,398.8
XS Rating Curve= 0 ,0
Exp/Cntr=0.3,0.1

Type RM Length L Ch R = 1 ,3723.3  ,292.2,293.7,293.6
XS GIS Cut Line= 3
     2008755.208      277214.283     2008828.993      277309.769
     2008885.417      277743.797
#Sta/Elev= 30
       0  1621.2    35.9 1595.33    52.2 1581.85    65.2 1572.65      75 1562.78
    88.1  1553.7   101.1 1546.16   117.4  1539.6     137 1533.77   150.1 1532.01
  167.59 1532.04  202.571533.007   231.7 1532.48   244.8 1527.76     255 1526.56
   264.4  1526.5     270  1526.7   277.4 1527.67   287.2 1532.38  301.881533.742
  339.51 1535.17  356.011535.774  393.411536.766  429.911539.225   447.3 1544.22
   460.4 1550.75   476.7 1560.61   532.2 1597.36   545.3 1609.91   558.4 1618.77
#Mann= 10 ,-1 , 0
       0     .12       0  167.59     .06       0  202.57     .12       0
     255    .045       0     270     .12       0  301.88    .016       0
  339.51     .08       0  356.01     .06       0  393.41     .08       0
  429.91     .12       0
Bank Sta=255,270
XS Rating Curve= 0 ,0
Exp/Cntr=0.3,0.1