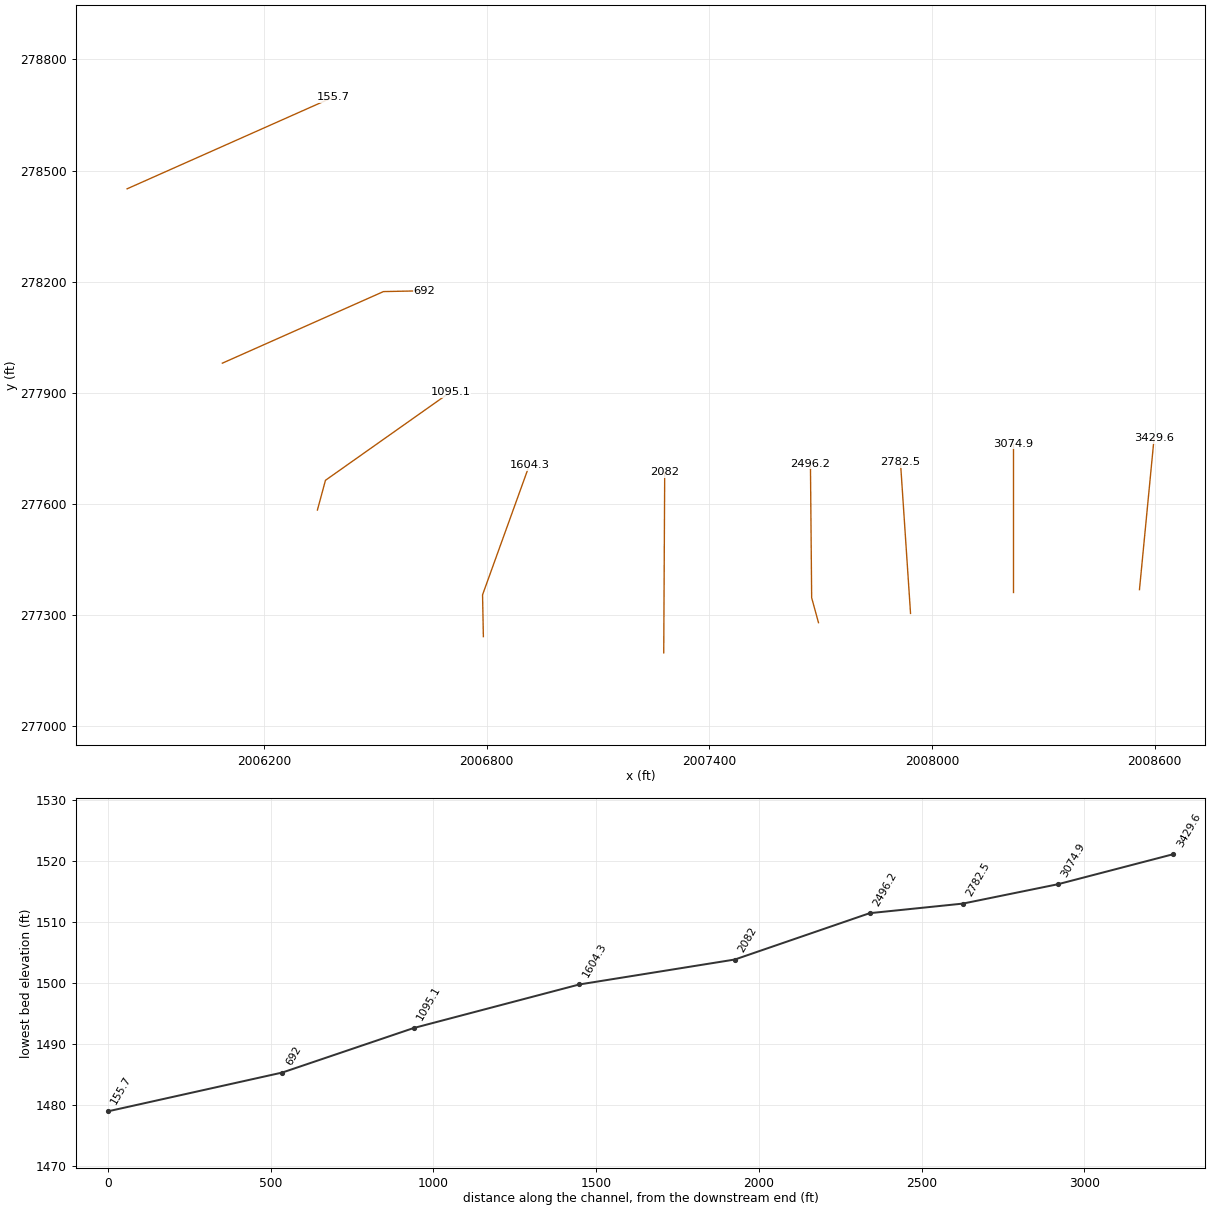
HEC-RAS study LAURELCK.prj: LAURELCK

--- LAURELCK.g01 (geometry) --- (continued)

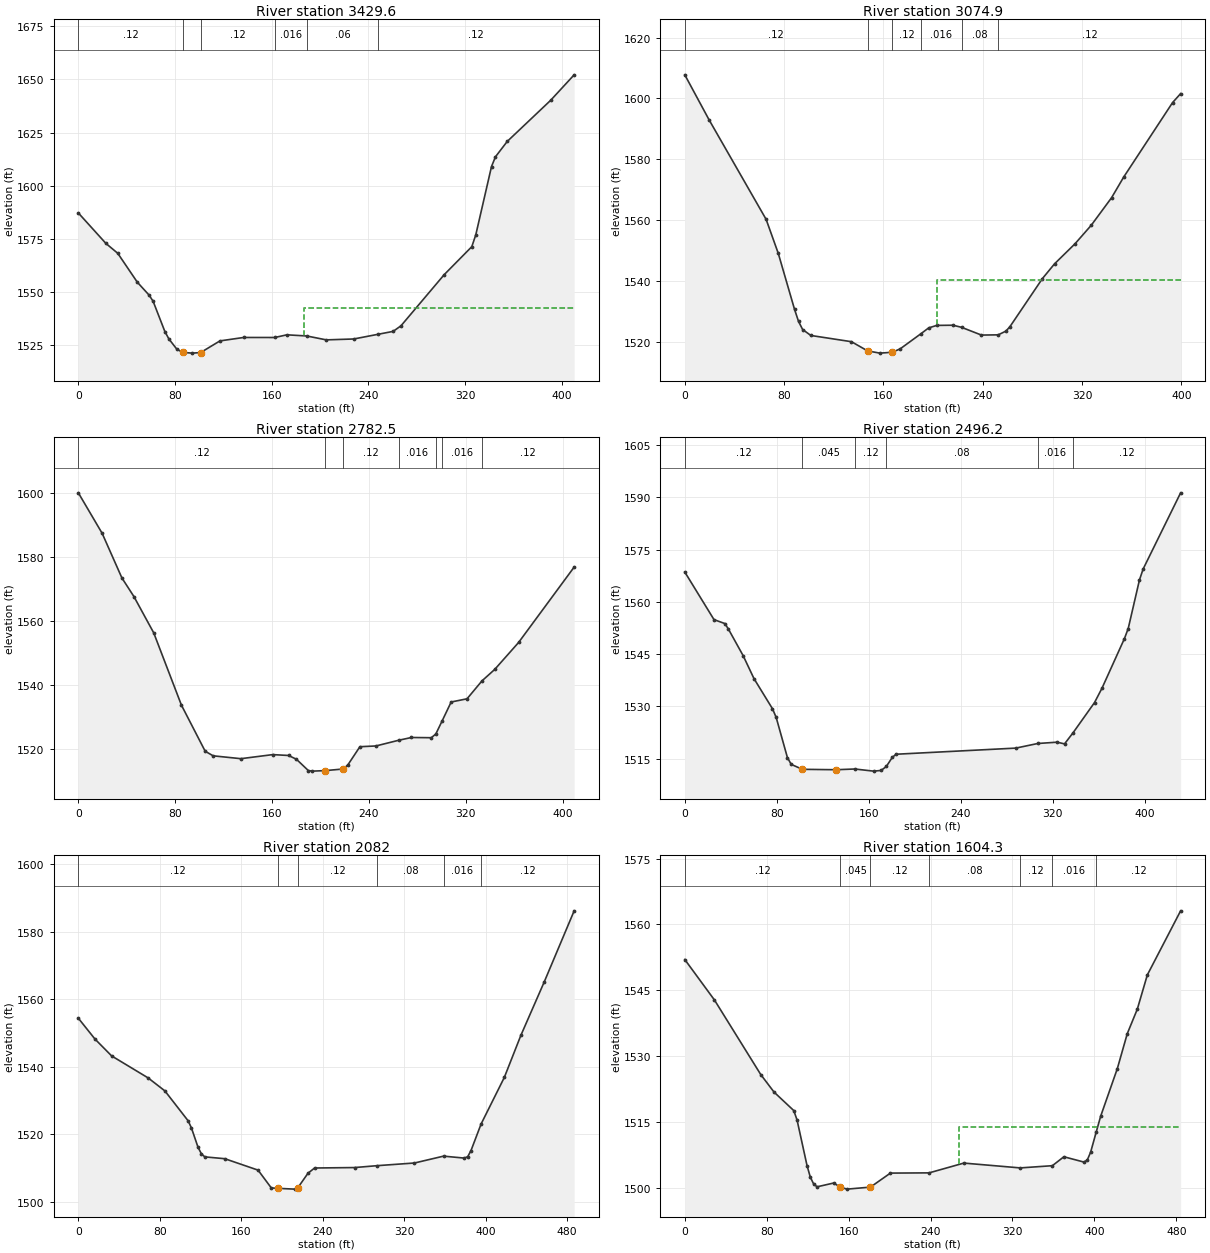
Type RM Length L Ch R = 1 ,3429.6  ,352.2,354.7,356.6
XS GIS Cut Line= 2
     2008558.673      277369.236     2008598.011      277777.646
#Sta/Elev= 30
       0 1587.13    22.8 1572.79    32.6 1568.14    48.8 1554.52    58.6  1548.4
    61.9 1545.51    71.6 1531.29    74.9 1527.82    81.4 1523.05    86.2 1521.45
    94.4 1521.11   101.2 1521.38   117.2 1526.87   136.8 1528.48  162.49 1528.47
   172.6 1529.73  188.981529.192   205.2 1527.35   227.9 1527.77  248.331530.017
   260.5 1531.35     267 1533.98   302.8 1558.09   325.6 1571.24   328.9 1576.81
   341.9 1608.97   345.2 1613.58   354.9 1620.79   390.8 1640.14   410.3 1652.17
#Mann= 6 ,-1 , 0
       0     .12       0    86.2    .045       0   101.2     .12       0
  162.49    .016       0  188.98     .06       0  248.33     .12       0
#XS Ineff= 2 , 0
                          186.79         1542.47
Permanent Ineff=
       F       F
Bank Sta=86.2,101.2
XS Rating Curve= 0 ,0
Exp/Cntr=0.3,0.1

Type RM Length L Ch R = 1 ,3074.9  ,290.7,292.3,293.7
XS GIS Cut Line= 2
     2008219.184      277364.022     2008219.184      277763.328
#Sta/Elev= 30
       0 1607.73    19.6 1592.89    65.5 1560.18    75.3 1548.97    88.4 1530.55
    91.6 1526.61    94.9 1523.95   101.5 1521.99   134.2 1519.94   147.3  1516.9
   157.1 1516.18   167.2 1516.46   173.5  1517.6  190.011522.516   196.4 1524.48
   202.9  1525.3     216 1525.36  222.851524.672   238.9 1522.12  252.391522.193
   258.6 1523.42   261.8 1524.86     288 1540.71   297.8 1545.57   314.2 1552.13
   327.3 1558.23   343.7 1567.31   353.5 1574.13   392.8 1598.59   399.3 1601.55
#Mann= 6 ,-1 , 0
       0     .12       0   147.3    .045       0   167.2     .12       0
  190.01    .016       0  222.85     .08       0  252.39     .12       0
#XS Ineff= 2 , 0
                          202.84         1540.36
Permanent Ineff=
       F       F
Bank Sta=147.3,167.2
XS Rating Curve= 0 ,0
Exp/Cntr=0.3,0.1

Type RM Length L Ch R = 1 ,2782.5  ,289.9,286.3,282.4
XS GIS Cut Line= 2
     2007941.969      277305.085     2007914.801      277713.759
#Sta/Elev= 30
       0 1599.96    19.7 1587.29      36 1573.36    45.9 1567.56    62.3 1556.19
    85.2 1533.59   104.8 1519.21   111.4 1517.78   134.3 1516.89   160.6 1518.16
   173.7 1517.89   180.2  1516.7     190 1513.18   193.3    1513     204 1513.16
     219 1513.67   222.8 1515.03   232.6 1520.63   245.8 1520.86  264.621522.643
   275.2 1523.51   291.6 1523.44  295.311524.603  300.391528.576     308  1534.6
   321.1  1535.6  333.491541.212     344 1544.79   363.7  1553.2   409.6 1576.76
#Mann= 7 ,-1 , 0
       0     .12       0     204    .045       0     219     .12       0
  264.62    .016       0  295.31     .12       0  300.39    .016       0
  333.49     .12       0
Bank Sta=204,219
XS Rating Curve= 0 ,0
Exp/Cntr=0.3,0.1

Type RM Length L Ch R = 1 ,2496.2  ,411.7,414.2,416.4
XS GIS Cut Line= 3
      2007693.98      277280.149     2007675.612      277347.434
     2007672.309      277709.074
#Sta/Elev= 30
       0 1568.59    25.4 1554.93    34.9 1553.79      38 1552.18    50.7 1544.62
    60.2 1537.99    76.3 1529.33    79.5 1526.86    89.3  1515.3    92.6 1513.37
   102.3 1511.95   131.6 1511.83   147.9 1512.04   164.2 1511.43   170.8 1511.62
  175.341512.766   180.5 1515.36   183.8 1516.28     288 1518.04  307.121519.364
   323.9 1519.74   330.4 1519.25  337.931522.494   356.5 1531.12     363 1535.25
   382.5 1549.47   385.8 1552.37   395.6 1566.34   398.8 1569.47   431.4 1591.33
#Mann= 6 ,-1 , 0
       0     .12       0   102.3    .045       0   147.9     .12       0
  175.34     .08       0  307.12    .016       0  337.93     .12       0
Bank Sta=102.3,131.6
XS Rating Curve= 0 ,0
Exp/Cntr=0.3,0.1

Type RM Length L Ch R = 1 ,2082    ,487.4,477.8,467.2
XS GIS Cut Line= 2
     2007277.127      277198.686      2007279.73      277685.608
#Sta/Elev= 30
       0 1554.39    16.3 1548.24    32.7 1543.24    68.6 1536.72      85 1532.89
   107.8 1524.05   111.1 1521.91   117.6 1516.16   120.9 1514.26   124.2 1513.37
   143.8 1512.83   176.5 1509.45   189.5 1504.18   196.1 1504.06   212.4 1503.83
   215.7  1504.3   225.5 1508.52     232 1510.08   271.2 1510.21  293.551510.772
   330.1 1511.56  358.641513.588   379.1 1513.01   382.4 1513.44   385.6 1515.24
  395.511523.098   418.3 1536.86   434.6 1549.34   457.5 1565.12   486.9 1586.16
#Mann= 6 ,-1 , 0
       0     .12       0   196.1    .045       0   215.7     .12       0
  293.55     .08       0  358.64    .016       0  395.51     .12       0
Bank Sta=196.1,215.7
XS Rating Curve= 0 ,0
Exp/Cntr=0.3,0.1

Type RM Length L Ch R = 1 ,1604.3  ,520.5,509.1,497
XS GIS Cut Line= 3
     2006791.232      277242.495     2006789.062      277355.342
      2006914.93      277704.734
#Sta/Elev= 30
       0 1552.02      29 1542.79    74.2 1525.82    87.1 1521.85   106.4 1517.63
   109.6 1515.51   119.4 1505.07   122.6 1502.45   125.9 1500.88   129.2 1500.27
   145.4 1501.13     152 1500.16   158.5 1499.74   181.3  1500.2   200.8 1503.39
  238.591503.443   272.5 1505.67  327.551504.572  358.951505.075   370.2 1507.11
   389.8  1505.9     393 1506.35   396.3 1508.14  401.761512.726   406.1 1516.33
   422.4 1527.19   432.1 1535.14   441.9 1540.72   451.7 1548.52   484.2 1563.11
#Mann= 7 ,-1 , 0
       0     .12       0     152    .045       0   181.3     .12       0
  238.59     .08       0  327.55     .12       0  358.95    .016       0
  401.76     .12       0
#XS Ineff= 2 , 0
                          267.76         1513.95
Permanent Ineff=
       F       F
Bank Sta=152,181.3
XS Rating Curve= 0 ,0
Exp/Cntr=0.3,0.1

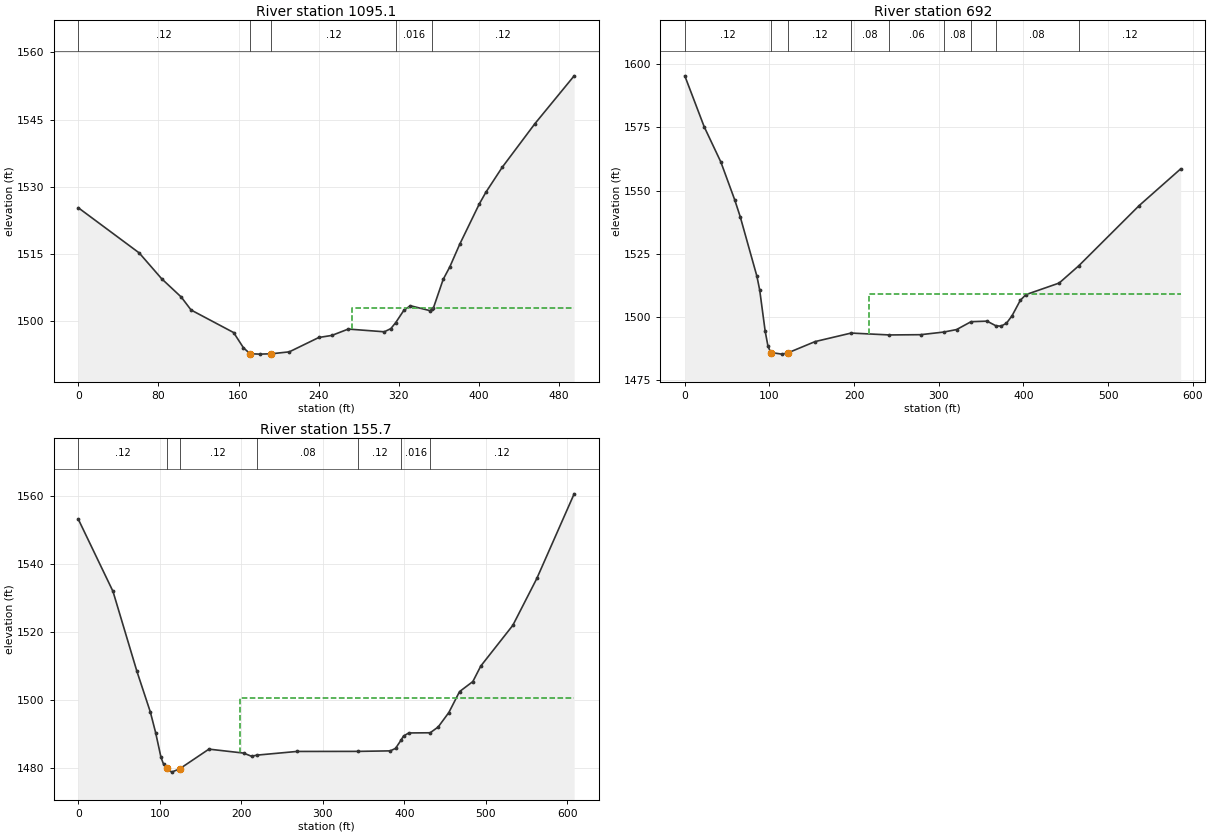
Type RM Length L Ch R = 1 ,1095.1  ,407.3,403.1,398.3
XS GIS Cut Line= 3
     2006344.154      277583.969     2006365.855      277664.264
     2006702.257      277902.217
#Sta/Elev= 30
       0 1525.29    60.8  1515.2    83.2 1509.44   102.8 1505.34   112.6 1502.45
   155.1 1497.41   164.9 1494.01   171.5 1492.68   181.3 1492.59   192.8 1492.67
   210.7  1493.1   240.2 1496.31   253.2 1496.77   269.6 1498.19   305.6 1497.58
   312.1 1498.29  316.97 1499.63   325.2 1502.41   331.7  1503.4   351.3  1502.3
  352.871502.581   354.6 1502.89   364.4  1509.3     371 1512.08   380.8 1517.09
   400.4 1526.12   406.9 1528.71   423.3 1534.32     456 1544.08   495.2 1554.77
#Mann= 5 ,-1 , 0
       0     .12       0   171.5    .045       0   192.8     .12       0
  316.97    .016       0  352.87     .12       0
#XS Ineff= 2 , 0
                          273.44         1502.84
Permanent Ineff=
       F       F
Bank Sta=171.5,192.8
XS Rating Curve= 0 ,0
Exp/Cntr=0.3,0.1

Type RM Length L Ch R = 1 ,692     ,536.2,536.3,536.2
XS GIS Cut Line= 3
     2006088.107      277980.342     2006522.135      278173.484
     2006632.812      278175.654
#Sta/Elev= 30
       0 1595.43    22.9 1575.28    42.6 1561.32      59 1546.33    65.5 1539.66
    85.2 1516.11    88.5 1510.64      95 1494.28    98.3 1488.38   101.6 1485.94
   114.7  1485.3   121.6 1485.77     154 1490.27  196.541493.637  241.77 1492.89
   278.5 1492.99  305.871494.031   321.1 1495.02   338.21498.136   357.1 1498.35
  367.461496.532   373.5 1496.36     380 1497.51   386.6 1500.47   396.4  1506.6
     403 1508.84   442.3 1513.43  465.471520.265   536.9 1544.11   585.8 1558.59
#Mann= 9 ,-1 , 0
       0     .12       0   101.6    .045       0   121.6     .12       0
  196.54     .08       0  241.77     .06       0  305.87     .08       0
   338.2    .016       0  367.46     .08       0  465.47     .12       0
#XS Ineff= 2 , 0
                          217.33          1509.2
Permanent Ineff=
       F       F
Bank Sta=101.6,121.6
XS Rating Curve= 0 ,0
Exp/Cntr=0.3,0.1

Type RM Length L Ch R = 1 ,155.7   ,160.6,155.7,150.9
XS GIS Cut Line= 2
     2005831.597      278450.828     2006387.153      278698.224
#Sta/Elev= 30
       0 1553.14    42.5 1531.98    71.9 1508.48    88.3  1496.6    94.8 1490.54
   101.4 1483.26   104.6 1481.22   109.3 1480.11   114.4 1478.93   124.3  1479.9
   160.2 1485.68   202.7 1484.52   212.5 1483.58   219.1 1483.92   268.1    1485
   343.3 1485.02   382.6 1485.17   389.1  1485.9   395.6 1488.23   398.9 1489.53
   405.4 1490.43   431.6 1490.48   441.4 1492.18   454.5 1496.43   467.6 1502.56
   483.9 1505.51   493.7 1510.08     533 1522.03   562.4 1535.77   608.2 1560.61
#Mann= 7 ,-1 , 0
       0     .12       0   109.3    .045       0   124.3     .12       0
   219.1     .08       0   343.3     .12       0   395.6    .016       0
   431.6     .12       0
#XS Ineff= 2 , 0
                          198.86         1500.82
Permanent Ineff=
       F       F
Bank Sta=109.3,124.3
XS Rating Curve= 0 ,0
Exp/Cntr=0.3,0.1

Chan Stop Cuts=-1
Use User Specified Reach Order=0
Composite Channel Slope=5